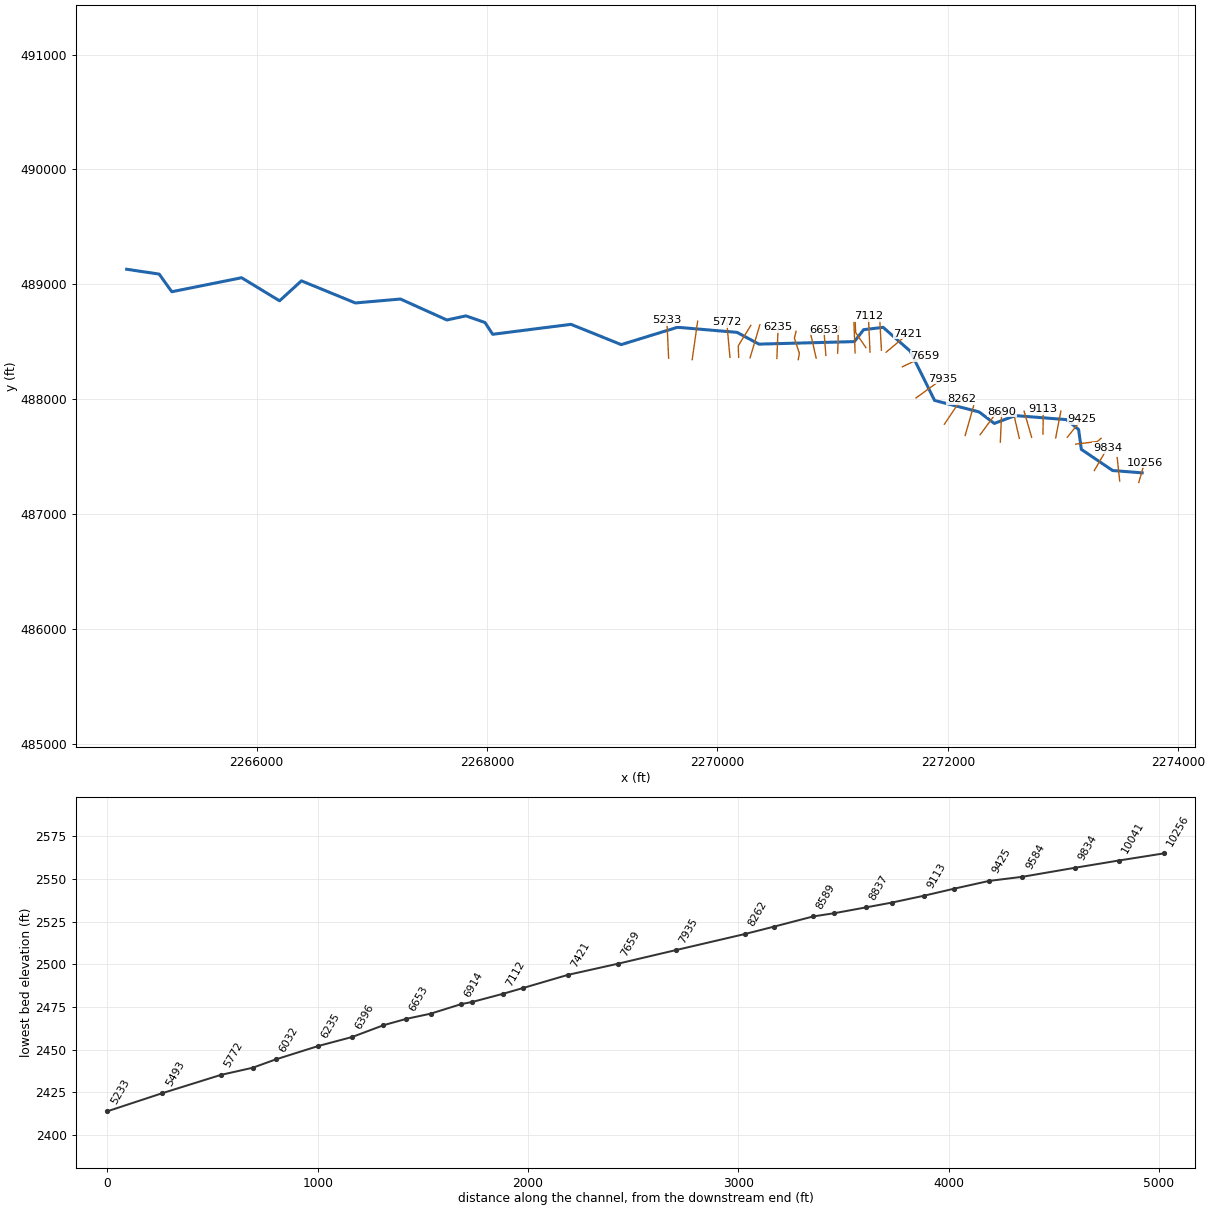
--- LAURELRN2.prj (project) ---

Proj Title=LAURELRN2
Current Plan=p01
Default Exp/Contr=0,0
English Units
Geom File=g01
Flow File=f01
Plan File=p01
BEGIN DESCRIPTION:
----------MODEL BY WOOD PLC 2021----------
Stream Name: Laurel Run II
Flood Zone: Enhanced Approximate
Pocahontas County, WV
HEC-RAS Version: RAS 6.1
Vertical Datum: NAVD88
Projection: NAD 1983 StatePlane West Virginia S FIPS 4702 (US Feet)
Terrain: 1-meter LIDAR (FEMA Region III 3DEP collected 2016-2018)
Land Use: 2019 NLCD
Hydrologic Method:
WV SIR2010-5033 regression equations
END DESCRIPTION:
DSS Export Rating Curves= 0
DSS Export Rating Curve Sorted= 0
DSS Export Volume Flow Curves= 0
DXF OffsetX= 0
DXF OffsetY= 0
DXF ScaleX= 0
DXF ScaleY= 0

--- LAURELRN2.p01 (plan) ---

Plan Title=Floodplain
Program Version=6.10
Short Identifier=Floodplain
Geom File=g01
Flow File=f01
Subcritical Flow
K Sum by GR= 0
Std Step Tol= 0.01
Critical Tol= 0.01
Num of Std Step Trials= 20
Max Error Tol= 0.3
Flow Tol Ratio= 0.001
Split Flow NTrial= 30
Split Flow Tol= 0.02
Split Flow Ratio= 0.02
Log Output Level= 0
Friction Slope Method= 1
Unsteady Friction Slope Method= 2
Unsteady Bridges Friction Slope Method= 1
Parabolic Critical Depth
Global Vel Dist= 0 , 0 , 0
Global Log Level= 0
CheckData=True
Encroach Param=-1 ,0,0, 0
Mapping Interval=1HOUR
Computation Time Step Use Courant=        0
Computation Time Step Use Time Series=    0
Computation Time Step Count To Double=0
Computation Time Step Max Doubling=0
Computation Time Step Max Halving=0
Computation Time Step Residence Courant=0
Run HTab= 0
Run UNet= 0
Run Sediment= 0
Run PostProcess= 0
Run WQNet= 0
Run RASMapper= 0
UNET Theta= 0
UNET Theta Warmup= 0
UNET ZTol= 0
UNET ZSATol= 0
UNET MxIter= 0
UNET Max Iter WO Improvement= 0
UNET MaxInSteps= 0
UNET DtIC= 0
UNET DtMin= 0
UNET MaxCRTS= 0
UNET WFStab= 0
UNET SFStab= 0
UNET WFX= 1
UNET SFX= 1
UNET Gravity=32.174
UNET 1D Methodology=Finite Difference
UNET DSS MLevel= 1
UNET Pardiso=0
UNET DZMax Abort= 0
UNET Use Existing IB Tables= 0
UNET Froude Reduction=False
UNET Froude Limit= 0
UNET Froude Power= 0
UNET D1 Cores= 0
UNET WindReference=Eulerian
UNET WindDragFormulation=Hsu (1988)
UNET D2 Coriolis=0
UNET D2 Cores= 0
UNET D2 Theta= 1
UNET D2 Theta Warmup= 1
UNET D2 Z Tol= 0.01
UNET D2 Volume Tol= 0.01
UNET D2 Max Iterations= 20
UNET D2 Equation= 0
UNET D2 RampUpFraction=0.1
UNET D2 TimeSlices= 1
UNET D2 Turbulence Formulation=Non-Conservative (original)
UNET D2 Eddy Viscosity=0.3
UNET D2 Transverse Eddy Viscosity=0.1
UNET D2 Smagorinsky Mixing=0
UNET D2 BCVolumeCheck=0
UNET D2 Cores=0
UNET D2 SolverType=PARDISO (Direct)
UNET D2 Minimum Iterations= 2147483647
UNET D2 Maximum Iterations= 2147483647
UNET D2 Restart Number= 10
UNET D2 Relaxation Coeff=1.3
UNET D2 SOR Precondition Iterations= 10
UNET D2 ILUT Maximum Fill= 8
UNET D2 ILUT Tolerance=1E-08
UNET D1D2 MaxIter= 0
UNET D1D2 ZTol=0.01
UNET D1D2 QTol=0.1
UNET D1D2 MinQTol=1
Write IC File= 0
Write IC File at Fixed DateTime=0
Write IC File at Sim End=0
Echo Input=False
Echo Parameters=False
Echo Output=False
Write Detailed= 0
HDF Write Warmup=0
HDF Write Time Slices=0
HDF Flush=0
HDF Compression= 1
HDF Chunk Size= 1
HDF Spatial Parts= 1
HDF Use Max Rows=0
HDF Fixed Rows= 1
Calibration Method= 0
Calibration Iterations= 20
Calibration Max Change=0.05
Calibration Tolerance=0.2
Calibration Maximum=1.5
Calibration Minimum=0.5
Calibration Optimization Method= 1
WQ AD Non Conservative
WQ ULTIMATE=-1
WQ Max Comp Step=1HOUR
WQ Output Interval=15MIN
WQ Output Selected Increments= 0
WQ Output face flow=0
WQ Output face velocity=0
WQ Output face area=0
WQ Output face dispersion=0
WQ Output cell volume=0
WQ Output cell surface area=0
WQ Output cell continuity=0
WQ Output cumulative cell continuity=0
WQ Output face conc=0
WQ Output face dconc_dx=0
WQ Output face courant=0
WQ Output face peclet=0
WQ Output face adv mass=0
WQ Output face disp mass=0
WQ Output cell mass=0
WQ Output cell source sink temp=0
WQ Output nsm pathways=0
WQ Output nsm derived pathways=0
WQ Create Restart=0
WQ Fixed Restart=0
WQ System Summary=0
WQ Write To DSS=0
Sorting and Armoring Iterations= 10
XS Update Threshold= 0.02
Bed Roughness Predictor= 0
Hydraulics Update Threshold= 0.02
Energy Slope Method= 1
Volume Change Method= 1
Sediment Retention Method= 0
Sediment TS Multiplier= 1
Warm Up Method= 0
XS Weighting Method= 0
Number of US Weighted Cross Sections= 1
Number of DS Weighted Cross Sections= 1
Upstream XS Weight=0
Main XS Weight=1
Downstream XS Weight=0
Number of DS XS's Weighted with US Boundary= 1
Upstream Boundary Weight= 1
Weight of XSs Associated with US Boundary= 0
Number of US XS's Weighted with DS Boundary= 1
Downstream Boundary Weight= 0.5
Weight of XSs Associated with DS Boundary= 0.5
Percentile Method= 0
Sediment Output Level= 3
Mass or Volume Output= 0
Output Increment Type= 1
Profile and TS Output Increment= 1
Transport Output Increment 1
XS Output Flag= 0
XS Output Increment= 10
Read HDF5 Sediment Hotstart= 0
Sediment Hotstart Type= 0
Write Gradation File= 0
Read Gradation Hotstart= 0
Write HDF5 File= 1
Write Binary Output= 1
Write DSS Sediment File= 0
DSS Sediment Output Type= 1
SV Curve= 0
Specific Gage Flag= 0
Subcell Erosion Methods= 0
Subcell Deposition Methods= 0
Advection Scheme= 1
Matrix Solver= 0
Implicit Weighting Factor= 1
Maximum Outer Loop Convergence Iterations= 5
Convergence Maximum Absolute= 0.001
Convergence RMSE= 0.0001
Grain Fractions Max Abs Error= 0.001
Max Subgrid Regions= 1
Max Subgrid Length Scale= 3.402823E+38
Initial Layer Thickness= 3.402823E+38
Min Layer Thickness= 3.402823E+38
Max Layer Thickness= 3.402823E+38
Number of Layers= 5

--- LAURELRN2.f01 (steady flow) ---

Flow Title=Flow
Program Version=6.10
Number of Profiles= 6
Profile Names=01pct,10pct,04pct,02pct,0_2pct,01plus
River Rch & RM=LAURELRN2,Main            ,10256
     617     327     434     523     861     913
River Rch & RM=LAURELRN2,Main            ,4721
     809     433     572     687    1120    1200
Boundary for River Rch & Prof#=LAURELRN2,Main            , 1
Up Type= 0
Dn Type= 3
Dn Slope=0.02709
Boundary for River Rch & Prof#=LAURELRN2,Main            , 2
Up Type= 0
Dn Type= 3
Dn Slope=0.02709
Boundary for River Rch & Prof#=LAURELRN2,Main            , 3
Up Type= 0
Dn Type= 3
Dn Slope=0.02709
Boundary for River Rch & Prof#=LAURELRN2,Main            , 4
Up Type= 0
Dn Type= 3
Dn Slope=0.02709
Boundary for River Rch & Prof#=LAURELRN2,Main            , 5
Up Type= 0
Dn Type= 3
Dn Slope=0.02709
Boundary for River Rch & Prof#=LAURELRN2,Main            , 6
Up Type= 0
Dn Type= 3
Dn Slope=0.02709
DSS Import GetInterval= 0
DSS Import GetPeak= 0
DSS Import FillOption= 0

--- LAURELRN2.g01 (geometry) ---

Geom Title=Geometry
Program Version=6.10

River Reach=LAURELRN2       ,Main
Reach XY= 30
     2273686.611      487360.122     2273430.567      487380.442
     2273159.218      487564.169     2273134.841      487737.692
     2273030.385      487823.344     2272584.568      487858.564
     2272403.013      487790.204     2272272.068      487889.981
     2271884.923      487990.309     2271673.204      488419.479
     2271438.479      488626.266      2271269.13       488606.05
     2271188.751       488502.21     2270360.446      488480.336
     2270169.883        488582.7     2269653.163      488626.896
     2269164.942      488476.078     2268728.913      488652.455
     2268049.308      488565.9812267982.45822128488668.370605726
      2267816.97      488726.115     2267651.777488690.475419438
     2267248.682      488872.591     2266857.385      488838.567
     2266388.899      489030.945     2266199.254      488857.134
     2265869.915      489057.982     2265263.837      488936.134
     2265154.489      489089.617     2264872.326      489131.768

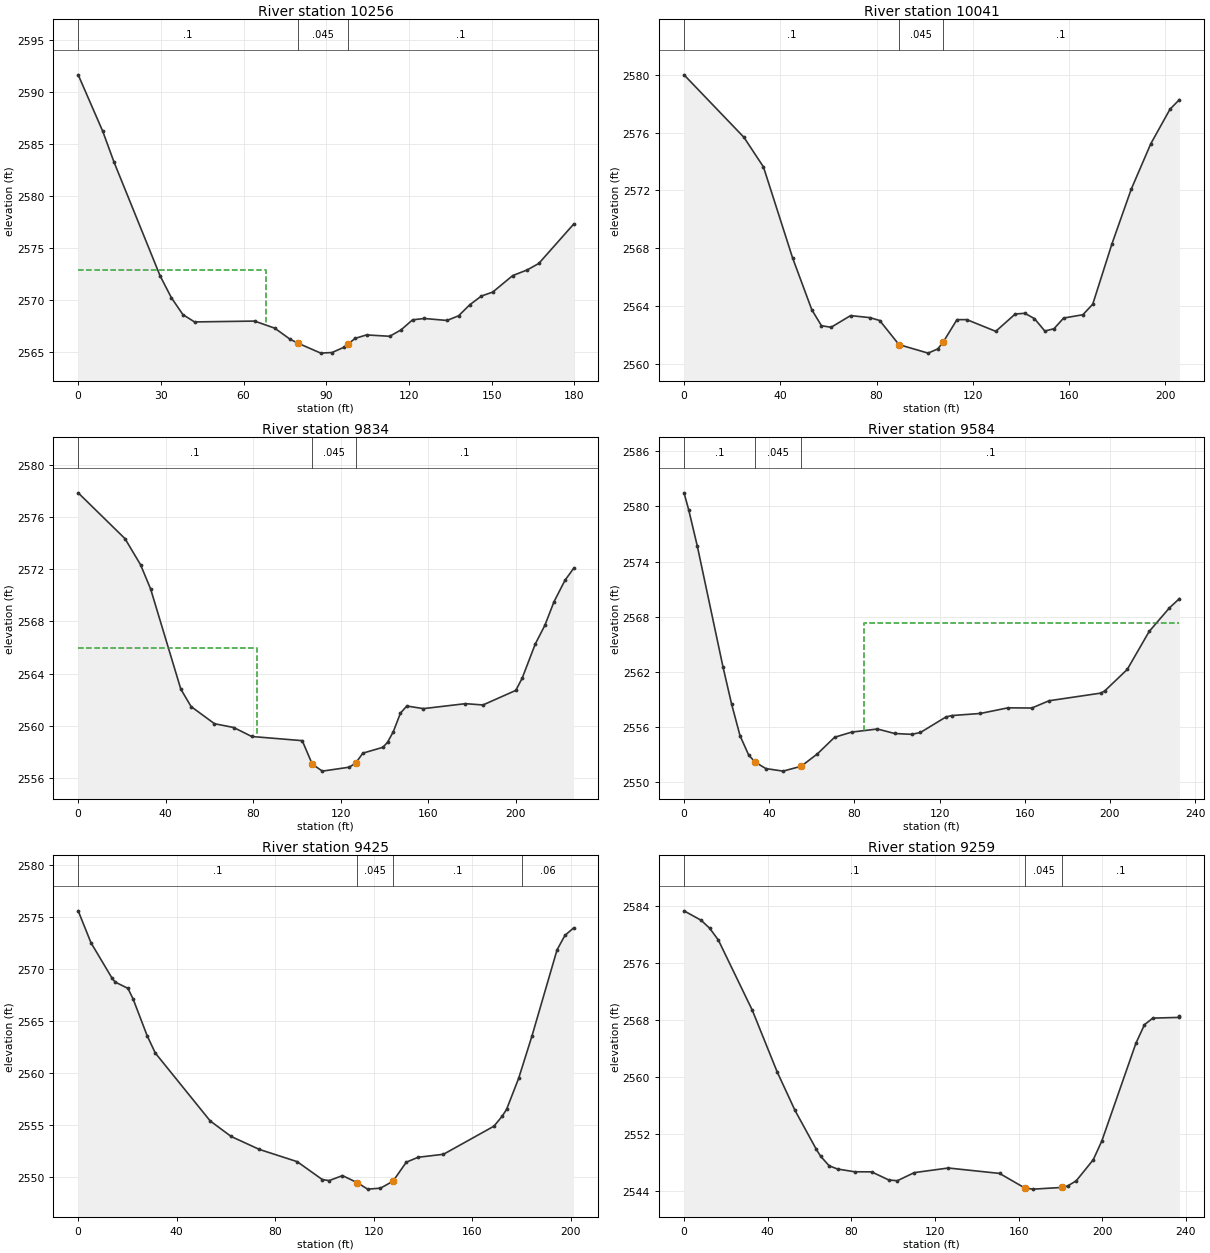
Type RM Length L Ch R = 1 ,10256   ,210.5,215,220.9
XS GIS Cut Line= 2
 2273657.4071657 487276.670074692273707.38298302487449.242818864
#Sta/Elev= 30
       0 2591.67     8.9 2586.25      13 2583.28    29.7 2572.36    33.8 2570.25
      38 2568.62    42.2 2567.92      64    2568    71.3 2567.32    76.9 2566.25
    79.7 2565.88      88 2564.92    92.1 2564.98    96.3 2565.47    97.7 2565.76
   100.5 2566.34   104.6 2566.67     113 2566.54   117.1 2567.15   121.3 2568.12
   125.5 2568.25   133.8 2568.06     138 2568.51   142.1 2569.58   146.3 2570.41
   150.4 2570.79   157.6 2572.37   162.9 2572.92   167.1 2573.54   179.7 2577.31
#Mann= 3 ,-1,0
       0      .1       0    79.7    .045       0    97.7      .1       0
#XS Ineff= 2 , 0
            68.2 2572.92
Permanent Ineff=
       F       F
Bank Sta=79.7,97.7
XS Rating Curve= 0 ,0
Exp/Cntr(USF)=0,0
Exp/Cntr=0.3,0.1

Type RM Length L Ch R = 1 ,10041   ,210.4,207,191.5
XS GIS Cut Line= 2
2273491.86227084487288.3831568742273469.99785076487492.971659017
#Sta/Elev= 30
       0 2580.01    24.9 2575.68      33 2573.63    45.1 2567.33    53.1 2563.73
    57.1 2562.63    61.1 2562.52    69.2 2563.33    77.2 2563.19    81.3 2562.99
    89.3 2561.32   101.4 2560.73   105.4 2561.02  107.582561.472   113.4 2563.05
   117.5 2563.05   129.5 2562.24   137.6 2563.44   141.6 2563.49   145.6 2563.12
   149.9 2562.26   153.7 2562.42   157.7 2563.16   165.7 2563.39   169.8 2564.12
   177.8 2568.31   185.8 2572.09   193.9 2575.23   201.9 2577.63   205.8 2578.29
#Mann= 3 ,-1,0
       0      .1       0    89.3    .045       0  107.58      .1       0
Bank Sta=89.3,107.58
XS Rating Curve= 0 ,0
Exp/Cntr(USF)=0,0
Exp/Cntr=0.3,0.1

Type RM Length L Ch R = 1 ,9834    ,257.4,249.8,226.9
XS GIS Cut Line= 2
2273271.65632579487380.526070053 2273384.8827869487576.524978595
#Sta/Elev= 30
       0 2577.88    21.4 2574.36    28.5 2572.36    33.1  2570.5    46.9 2562.81
    51.6 2561.47    62.3 2560.15    71.1 2559.86    79.3 2559.17   102.4 2558.85
     107 2557.04   111.6 2556.51   123.8 2556.81   126.8 2557.12   130.1 2557.89
   139.3 2558.34   141.4 2558.73     144 2559.53   147.3 2560.97   150.2 2561.51
   157.8 2561.31     177 2561.69     185 2561.59     200 2562.71   202.9 2563.64
   208.9 2566.27   213.3 2567.71   217.5 2569.53   222.5 2571.17   226.4 2572.07
#Mann= 3 ,-1,0
       0      .1       0     107    .045       0   126.8      .1       0
#XS Ineff= 2 , 0
           81.64 2565.99
Permanent Ineff=
       F       F
Bank Sta=107,126.8
XS Rating Curve= 0 ,0
Exp/Cntr(USF)=0,0
Exp/Cntr=0.3,0.1

Type RM Length L Ch R = 1 ,9584    ,153,158.6,172
XS GIS Cut Line= 3
2273110.01579165487610.1024808552273297.42510659487632.747773077
2273331.00260885487660.859170318
#Sta/Elev= 30
       0 2581.48     2.2 2579.63     6.2 2575.73    18.3 2562.56    22.3 2558.56
    26.3 2555.08    30.4 2552.96    33.5  2552.2    38.4 2551.51    46.5 2551.23
      55 2551.76    62.6  2553.1    70.7 2554.91    78.7 2555.47    90.8 2555.81
    98.9 2555.32   106.9 2555.23     111 2555.43     123 2557.12   125.7 2557.27
   139.2  2557.5   152.1 2558.11   163.3 2558.09   171.4 2558.88   195.7 2559.71
   197.6 2559.96   208.1 2562.28   218.4 2566.41   227.9 2568.97   232.6 2569.98
#Mann= 3 ,-1,0
       0      .1       0    33.5    .045       0      55      .1       0
#XS Ineff= 2 , 0
                            84.3         2567.32
Permanent Ineff=
       F       F
Bank Sta=33.5,55
XS Rating Curve= 0 ,0
Exp/Cntr(USF)=0,0
Exp/Cntr=0.3,0.1

Type RM Length L Ch R = 1 ,9425    ,162.1,166.4,173.9
XS GIS Cut Line= 2
2273036.61380996487669.448763919 2273162.3342254487826.404065182
#Sta/Elev= 30
       0 2575.55     5.2 2572.48    13.7  2569.1      15 2568.71    20.2  2568.1
    22.3 2567.08      28 2563.55    31.3 2561.89    53.6 2555.36    62.1 2553.87
    73.5 2552.63    88.9 2551.45    99.1 2549.73   101.9 2549.63   107.3 2550.11
   113.3 2549.43   117.5 2548.81   122.7  2548.9   127.8 2549.57   133.2  2551.4
     138 2551.87   148.3 2552.16   168.8 2554.86   172.1 2555.81   173.9 2556.47
   178.8 2559.45   184.2 2563.51   194.4  2571.8   197.6 2573.19   201.1  2573.9
#Mann= 4 ,-1,0
       0      .1       0   113.3    .045       0   127.8      .1       0
     180     .06       0
Bank Sta=113.3,127.8
XS Rating Curve= 0 ,0
Exp/Cntr(USF)=0,0
Exp/Cntr=0.3,0.1

Type RM Length L Ch R = 1 ,9259    ,143.9,145.4,148
XS GIS Cut Line= 2
 2272936.0199613487665.1052018652272981.48781175487897.640779867
#Sta/Elev= 30
       0 2583.39     8.2 2582.06    12.3 2580.93    16.4 2579.29    32.7 2569.38
    44.5 2560.77    53.1 2555.31    63.3 2549.83    65.3 2548.89    69.4 2547.53
    73.4 2547.08    81.6 2546.69    89.7 2546.68    97.9 2545.54     102 2545.43
   110.1 2546.57   126.4 2547.22   150.9 2546.46   163.1 2544.39   167.1 2544.25
   180.9 2544.49   183.5  2544.7   187.6 2545.43   195.7 2548.38   199.8 2551.02
   216.1 2564.76   220.2 2567.38   224.2  2568.3   236.5  2568.4   236.9 2568.57
#Mann= 3 ,0,0
       0      .1       0   163.1    .045       0   180.9      .1       0
Bank Sta=163.1,180.9
XS Rating Curve= 0 ,0
Exp/Cntr(USF)=0,0
Exp/Cntr=0.3,0.1

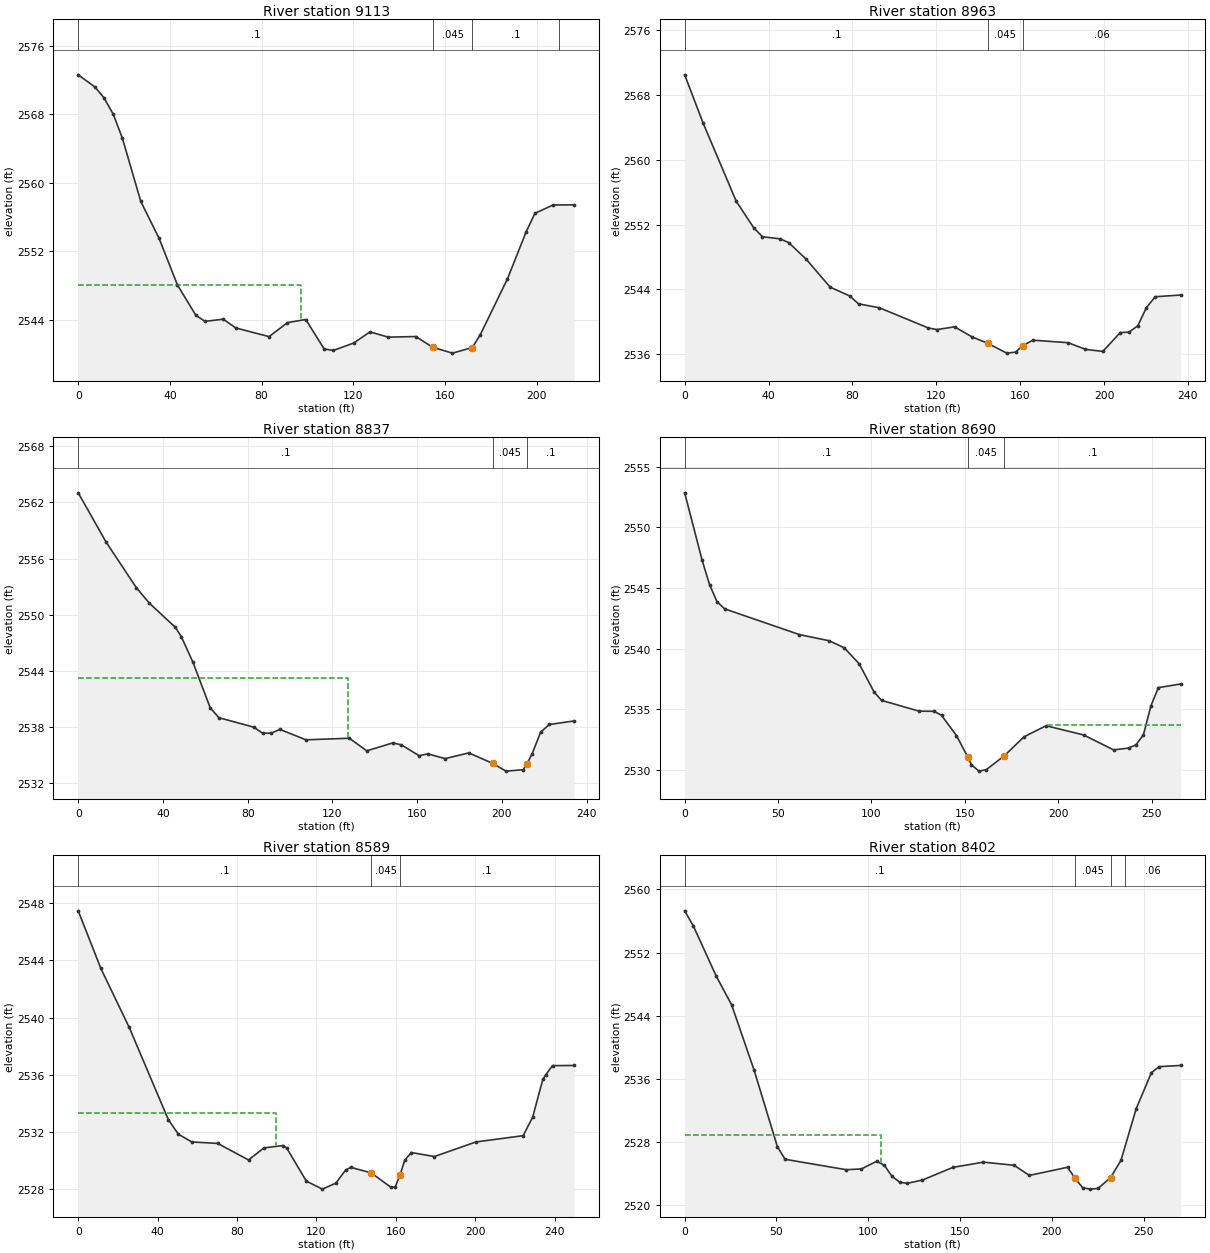
Type RM Length L Ch R = 1 ,9113    ,146.5,150.1,154.3
XS GIS Cut Line= 2
2272826.07825411487697.9115000682272828.22056453487914.284851794
#Sta/Elev= 30
       0 2572.62     7.3  2571.2    11.3 2569.91    15.3 2568.01    19.3 2565.19
    27.3 2557.82    35.3 2553.49    43.3 2548.05    51.3 2544.52    55.3 2543.79
    63.3 2544.05    68.7 2543.03    83.3 2542.01    91.3 2543.65    99.3 2544.01
   107.3 2540.57   111.3 2540.39   120.2 2541.26   127.3 2542.56   135.3 2541.95
   147.3 2542.02   154.7 2540.76   163.3 2540.08  171.952540.736   175.3 2542.16
   187.3 2548.76   195.4 2554.23   199.3 2556.43   207.2  2557.4   216.4 2557.42
#Mann= 4 ,-1,0
       0      .1       0   154.7    .045       0  171.95      .1       0
     210     .06       0
#XS Ineff= 2 , 0
           97.27 2548.05
Permanent Ineff=
       F       F
Bank Sta=154.7,171.95
XS Rating Curve= 0 ,0
Exp/Cntr(USF)=0,0
Exp/Cntr=0.3,0.1

Type RM Length L Ch R = 1 ,8963    ,126.2,125.9,123.7
XS GIS Cut Line= 2
2272727.35670988487669.520335216 2272662.0116143487896.807624196
#Sta/Elev= 30
       0 2570.52     8.8 2564.55    24.6 2554.89    32.9 2551.63    37.1 2550.51
    45.4 2550.26    49.6 2549.79    57.9 2547.75    69.4 2544.28    78.7 2543.19
    82.9 2542.22    92.8 2541.74   116.2 2539.24   120.3 2539.04   128.7 2539.38
     137 2538.14   144.62537.328   153.6 2536.13   157.8 2536.25   161.22537.053
   166.1 2537.73   182.8 2537.42   191.1  2536.6   199.4 2536.34   207.7 2538.67
   211.9 2538.72   216.1 2539.52   220.2 2541.76   224.4  2543.1   236.5 2543.31
#Mann= 3 ,-1,0
       0      .1       0   144.6    .045       0   161.2     .06       0
Bank Sta=144.6,161.2
XS Rating Curve= 0 ,0
Exp/Cntr(USF)=0,0
Exp/Cntr=0.3,0.1

Type RM Length L Ch R = 1 ,8837    ,151.1,147.6,141.2
XS GIS Cut Line= 2
2272620.41645445487660.4210678392272567.92984933487888.577126836
#Sta/Elev= 30
       0 2563.03    13.1 2557.78    27.5 2552.86    33.6 2551.22    45.9 2548.63
    48.7 2547.62    54.1 2544.94    62.3 2540.03    66.4 2538.97    82.9 2537.95
      87 2537.31    91.1 2537.31    95.2 2537.72   107.5  2536.6     128 2536.77
   136.2 2535.42   148.5 2536.27   152.6 2536.06   160.9  2534.9     165  2535.1
   173.2 2534.59   184.4  2535.2   195.7 2534.07   201.9 2533.25   210.1  2533.4
  211.73 2534.01   214.2 2535.07   218.3 2537.43   222.4 2538.24   234.1 2538.62
#Mann= 3 ,-1,0
       0      .1       0   195.7    .045       0  211.73      .1       0
#XS Ineff= 2 , 0
          127.46 2543.25
Permanent Ineff=
       F       F
Bank Sta=195.7,211.73
XS Rating Curve= 0 ,0
Exp/Cntr(USF)=0,0
Exp/Cntr=0.3,0.1

Type RM Length L Ch R = 1 ,8690    ,106.6,101.1,90.9
XS GIS Cut Line= 2
2272455.55899348487627.850998904 2272467.8703883487893.019502713
#Sta/Elev= 30
       0 2552.84     9.3 2547.31    13.3 2545.28    17.3 2543.87    21.4 2543.28
    61.4 2541.16    77.4 2540.65    85.4 2540.07    93.4 2538.76   101.4 2536.43
   105.4 2535.74   125.5 2534.85   133.5 2534.84   137.5 2534.51   145.5 2532.84
  151.67 2531.04   153.5 2530.44   157.5 2529.91   161.5 2530.03   171.22531.188
   181.7 2532.74   193.5 2533.65   213.6 2532.89   229.6 2531.66   237.6 2531.81
   241.6 2532.08   245.6 2532.91   249.6 2535.29   253.6 2536.79   265.5 2537.09
#Mann= 3 ,-1,0
       0      .1       0  151.67    .045       0   171.2      .1       0
#XS Ineff= 2 , 0
                           194.4         2533.75
Permanent Ineff=
       F       F
Bank Sta=151.67,171.2
XS Rating Curve= 0 ,0
Exp/Cntr(USF)=0,0
Exp/Cntr=0.3,0.1

Type RM Length L Ch R = 1 ,8589    ,181.9,186.5,191.3
XS GIS Cut Line= 2
2272280.86025397487692.5557240352272428.67967248487893.932902869
#Sta/Elev= 30
       0 2547.47    11.4 2543.44    25.7 2539.31    45.4 2532.86    50.4 2531.85
    57.2  2531.3    70.2  2531.2    85.8 2530.04    93.5 2530.88     103 2531.05
     105 2530.88   114.9 2528.56     123    2528   129.8 2528.42   134.7 2529.34
   137.3 2529.52   147.6 2529.14   157.3 2528.15   159.6 2528.13  161.992528.958
   164.5 2530.03   167.8 2530.56   179.4 2530.28   200.3  2531.3   224.1 2531.74
   228.9 2533.03     234 2535.67   235.4 2535.98   238.9 2536.64   249.8 2536.65
#Mann= 3 ,-1,0
       0      .1       0   147.6    .045       0  161.99      .1       0
#XS Ineff= 2 , 0
           99.73 2533.31
Permanent Ineff=
       F       F
Bank Sta=147.6,161.99
XS Rating Curve= 0 ,0
Exp/Cntr(USF)=0,0
Exp/Cntr=0.3,0.1

Type RM Length L Ch R = 1 ,8402    ,143.5,139.7,135.2
XS GIS Cut Line= 2
2272150.07568928487684.5914234852272224.12333144487944.407711756
#Sta/Elev= 30
       0 2557.28     4.8 2555.32    17.2 2549.01    25.6 2545.35    37.8 2537.12
    50.5  2527.4    54.7  2525.8      88 2524.48    96.3 2524.58   104.6 2525.55
   108.8 2525.04   112.9 2523.65   117.1 2522.91   121.2 2522.75   129.5 2523.17
   146.2 2524.78   162.8 2525.44   179.5 2525.04   187.8 2523.76   208.6 2524.79
   212.7 2523.39   216.9 2522.18   221.1 2522.02   225.2 2522.11     232 2523.47
   237.7 2525.66     246 2532.22   254.3 2536.78   258.5 2537.54   270.2 2537.69
#Mann= 4 ,-1,0
       0      .1       0   212.7    .045       0     232      .1       0
     240     .06       0
#XS Ineff= 2 , 0
          107.21  2528.9
Permanent Ineff=
       F       F
Bank Sta=212.7,232
XS Rating Curve= 0 ,0
Exp/Cntr(USF)=0,0
Exp/Cntr=0.3,0.1

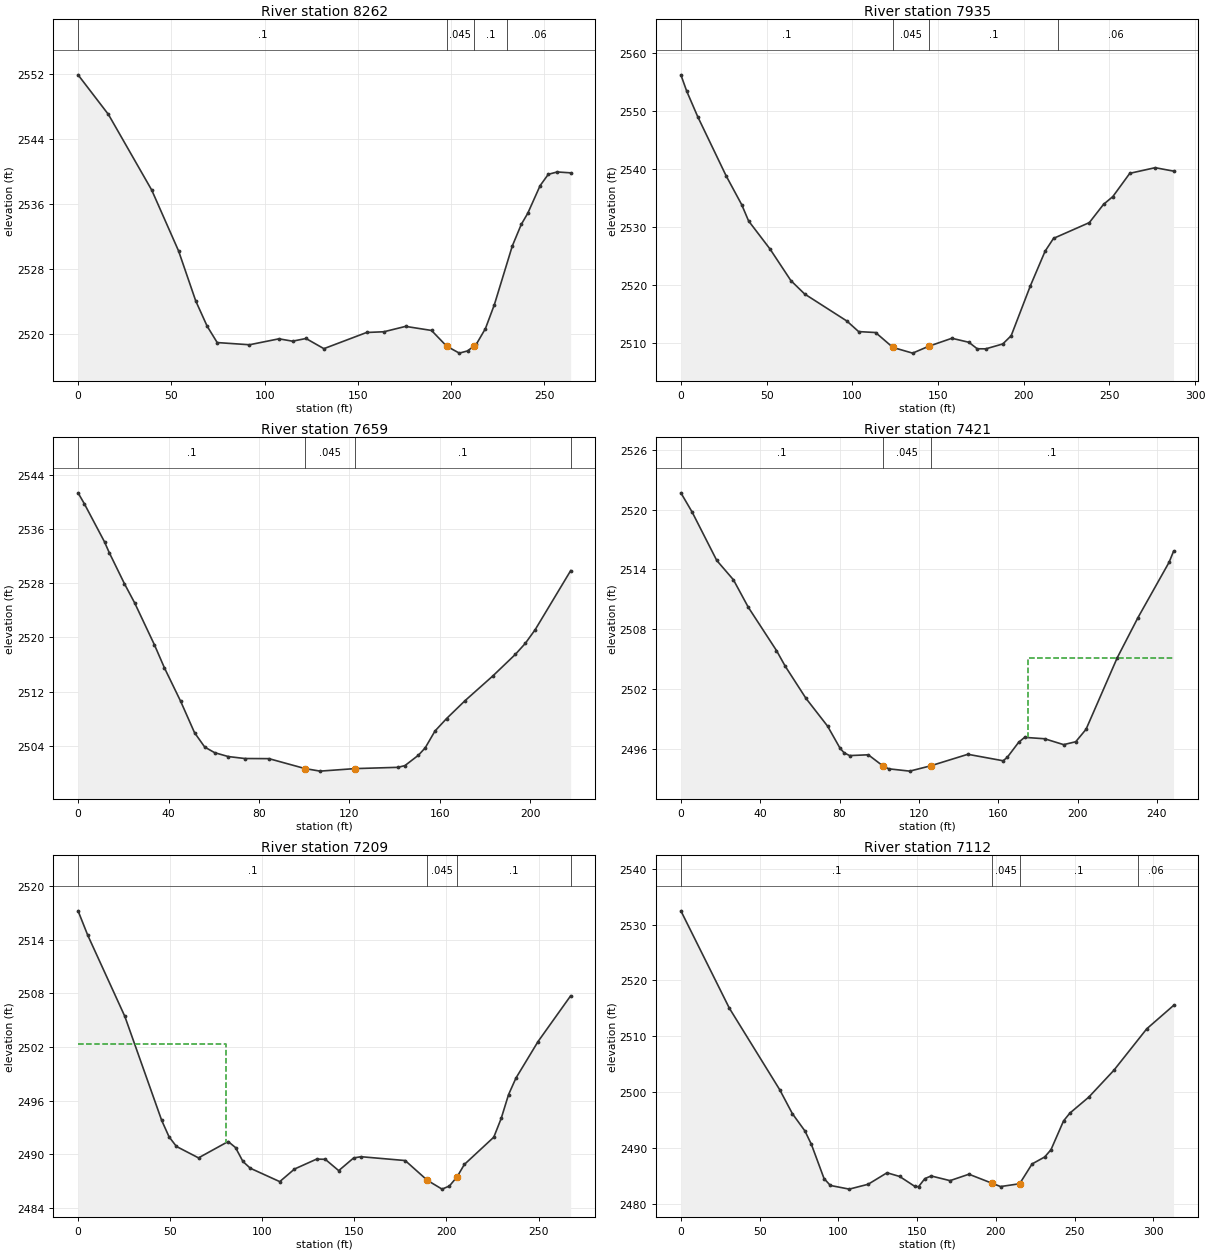
Type RM Length L Ch R = 1 ,8262    ,332.7,327.8,319.9
XS GIS Cut Line= 2
2271970.22524407487783.6039165932272116.97350737488003.190733939
#Sta/Elev= 30
       0  2551.9    16.3 2547.02    39.5 2537.72    53.9 2530.23    63.1 2524.08
    69.2 2520.98    74.6 2518.96    91.9 2518.69   107.7 2519.42     115 2519.13
   122.2 2519.46   131.8 2518.21   154.7  2520.2     164 2520.29   175.6 2520.95
   189.5 2520.45  197.592518.519   204.4 2517.66   208.8 2517.93   212.3 2518.54
   213.6 2518.79   218.4 2520.68   223.2 2523.63   232.8 2530.84   237.6 2533.49
   241.1 2534.87   247.7 2538.26   252.1 2539.66   256.9 2539.95   264.1 2539.84
#Mann= 4 ,-1,0
       0      .1       0  197.59    .045       0   212.3      .1       0
     230     .06       0
Bank Sta=197.59,212.3
XS Rating Curve= 0 ,0
Exp/Cntr(USF)=0,0
Exp/Cntr=0.3,0.1

Type RM Length L Ch R = 1 ,7935    ,278,275.5,272.4
XS GIS Cut Line= 2
2271724.21299191488012.3382068662271956.86790278 488181.15226742
#Sta/Elev= 30
       0  2556.2     3.4 2553.39     9.8 2549.01    26.4  2538.8    35.5 2533.82
    39.5 2531.03    52.1 2526.15    64.2 2520.74    72.2 2518.44    96.8 2513.79
   103.7 2511.96   113.6  2511.8   123.7 2509.23   135.2 2508.25   144.5 2509.42
   158.1 2510.81     168 2510.12   172.9    2509   177.9 2508.99   187.8 2509.83
   192.7 2511.25   203.9 2519.85   212.5 2525.82   217.4 2528.02   238.3 2530.74
   246.6 2533.89     252 2535.22   261.9 2539.23   276.7  2540.2   287.4 2539.61
#Mann= 4 ,-1,0
       0      .1       0   123.7    .045       0   144.5      .1       0
     220     .06       0
Bank Sta=123.7,144.5
XS Rating Curve= 0 ,0
Exp/Cntr(USF)=0,0
Exp/Cntr=0.3,0.1

Type RM Length L Ch R = 1 ,7659    ,229.3,238,239.8
XS GIS Cut Line= 2
2271605.63611054488283.2333586062271802.30020647488376.745208139
#Sta/Elev= 30
       0 2541.31     2.8 2539.69    11.7 2534.08    13.8 2532.49    20.5 2527.92
      25  2525.1    33.8 2518.88    38.2  2515.5    45.4 2510.55    51.5 2505.95
      56 2503.83    60.4    2503    66.4 2502.43    73.7 2502.14    84.4 2502.12
   100.3 2500.66     107 2500.28   122.4 2500.65   141.4 2500.84   144.5 2501.09
   150.5 2502.63   153.5 2503.72   157.8 2506.19   162.9 2508.02   171.1 2510.67
   183.5 2514.35   193.3 2517.48   197.7  2519.1   202.1 2521.13   217.8 2529.84
#Mann= 4 ,-1,0
       0      .1       0   100.3    .045       0   122.4      .1       0
  217.76     .06       0
Bank Sta=100.3,122.4
XS Rating Curve= 0 ,0
Exp/Cntr(USF)=0,0
Exp/Cntr=0.3,0.1

Type RM Length L Ch R = 1 ,7421    ,196.8,211.7,221.6
XS GIS Cut Line= 2
2271463.92227672 488409.522557462271653.83809484 488569.55314532
#Sta/Elev= 30
       0 2521.68     5.7 2519.74    18.1 2514.89    26.5 2512.95      34 2510.19
    48.2 2505.85    52.6 2504.28    63.1 2501.04      74 2498.25    80.2 2496.06
    82.3 2495.58    85.1  2495.3    94.5 2495.38   102.1 2494.23   104.9 2493.97
   115.4 2493.74   125.9 2494.27   144.7 2495.43   162.5 2494.78   164.6 2495.13
   170.3 2496.63   173.3 2497.13   183.4 2496.99     193  2496.4   199.1 2496.69
   204.3 2497.94     220 2505.11   230.5 2509.16   246.2 2514.72   248.4  2515.8
#Mann= 3 ,-1,0
       0      .1       0   102.1    .045       0   125.9      .1       0
#XS Ineff= 2 , 0
                             175         2505.14
Permanent Ineff=
       F       F
Bank Sta=102.1,125.9
XS Rating Curve= 0 ,0
Exp/Cntr(USF)=0,0
Exp/Cntr=0.3,0.1

Type RM Length L Ch R = 1 ,7209    ,98,97.9,97.7
XS GIS Cut Line= 2
2271423.43260991488427.8393114922271408.97201462488694.878304488
#Sta/Elev= 30
       0 2517.25     5.3  2514.5    25.4 2505.43    45.4 2493.79    49.4 2491.95
    53.4 2490.87    65.4 2489.59    81.5 2491.42    85.5 2490.74    89.5 2489.19
    93.5 2488.43   109.5 2486.93   117.5 2488.34   129.5 2489.45   134.2 2489.43
   141.5 2488.16   149.6 2489.58   153.6 2489.72   177.6 2489.29   189.6 2487.08
   197.6 2486.09   201.6 2486.44   205.8 2487.48   209.7 2488.85   225.7 2491.91
   229.7    2494   233.7 2496.67   237.7 2498.52   249.7 2502.61   267.4 2507.73
#Mann= 4 ,-1,0
       0      .1       0   189.6    .045       0   205.8      .1       0
  267.43     .06       0
#XS Ineff= 2 , 0
           80.29 2502.32
Permanent Ineff=
       F       F
Bank Sta=189.6,205.8
XS Rating Curve= 0 ,0
Exp/Cntr(USF)=0,0
Exp/Cntr=0.3,0.1

Type RM Length L Ch R = 1 ,7112    ,133.5,143.4,147.5
XS GIS Cut Line= 2
2271324.37228631488410.4067616042271310.69295873 488722.92678395
#Sta/Elev= 30
       0 2532.48    30.8 2515.03    62.8 2500.41    70.8 2496.14    78.8 2493.03
    82.9 2490.62    90.9 2484.52    94.9 2483.28   106.9 2482.62   118.9 2483.49
   130.9 2485.55   138.9 2484.89   148.6  2483.1   150.9 2483.05   154.9  2484.5
   158.9 2484.98   170.9 2484.14   182.9 2485.29   197.8 2483.65     203 2483.08
   215.12483.586     223 2487.13     231 2488.38     235 2489.68     243 2494.85
     247 2496.24     259  2499.1   274.9  2503.9   295.8 2511.34   312.8 2515.52
#Mann= 4 ,-1,0
       0      .1       0   197.8    .045       0   215.1      .1       0
     290     .06       0
Bank Sta=197.8,215.1
XS Rating Curve= 0 ,0
Exp/Cntr(USF)=0,0
Exp/Cntr=0.3,0.1

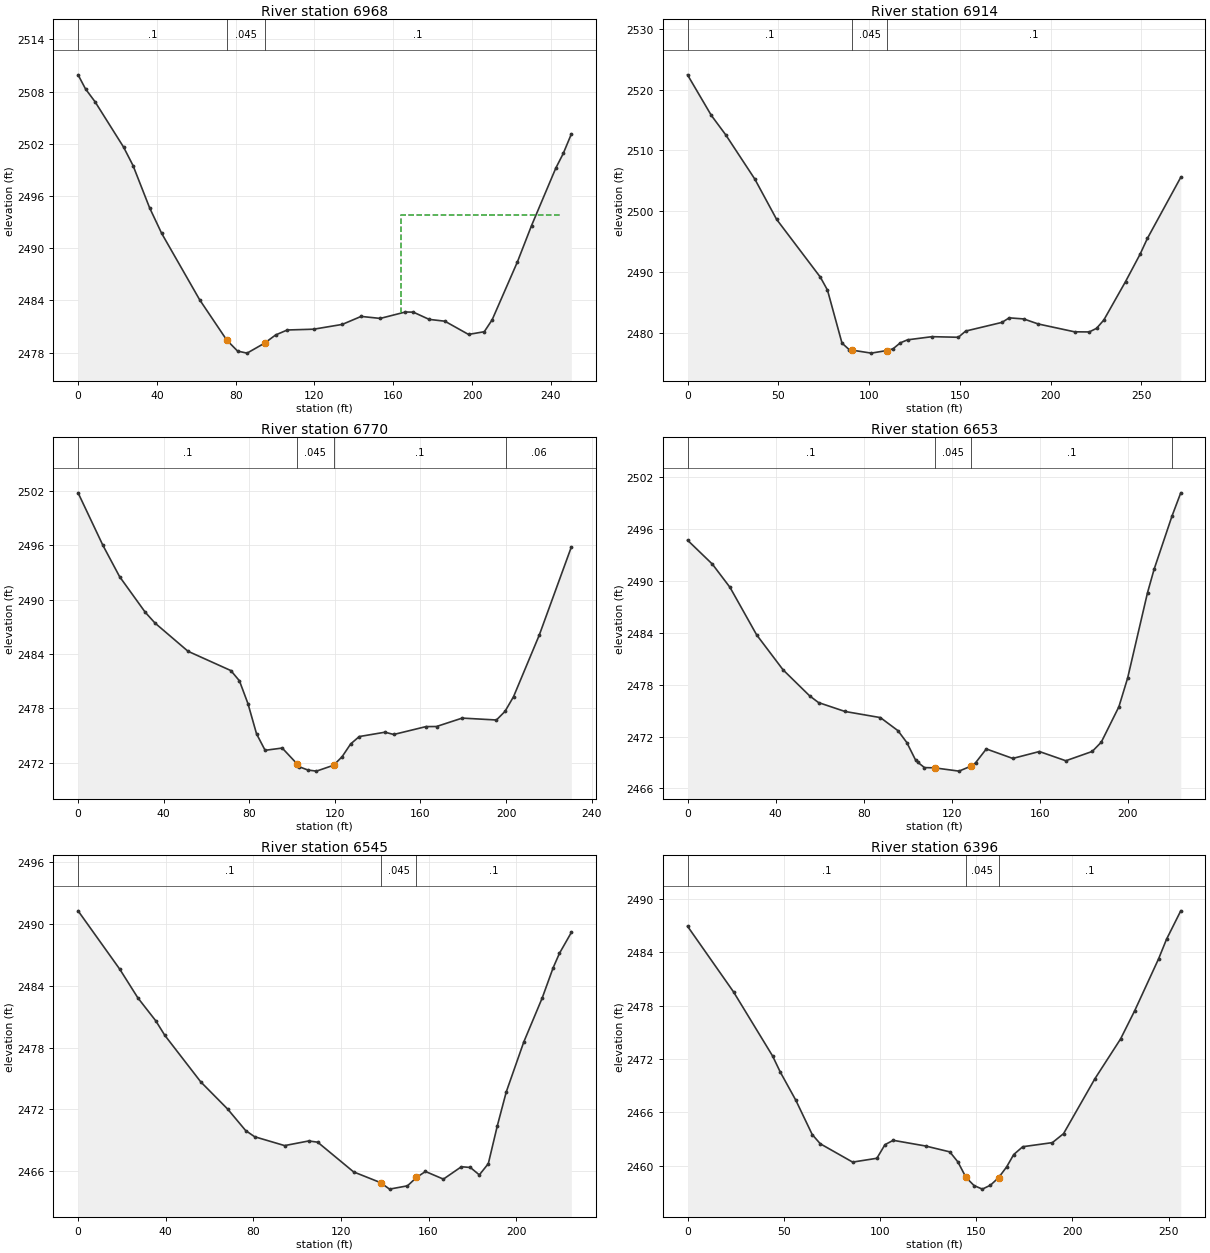
Type RM Length L Ch R = 1 ,6968    ,61.1,54.1,45
XS GIS Cut Line= 3
2271288.46705388488450.0122242682271200.20608214488580.872228338
2271195.50352027488673.329245095
#Sta/Elev= 30
       0 2509.92     3.8 2508.29     8.6 2506.83    23.1 2501.61    27.9 2499.49
    36.3 2494.64    42.4 2491.71    61.7 2484.0775.493582479.425      81 2478.16
    85.8 2477.9394.691952479.079   100.3 2480.02   106.2 2480.59   119.6 2480.68
   134.1 2481.23   143.7 2482.15   153.4 2481.92   166.2 2482.66   170.2 2482.64
   178.2 2481.81   186.2  2481.6   198.2 2480.08   206.2 2480.39   210.2 2481.76
     223  2488.4   230.2 2492.59   242.5 2499.19   246.3 2500.88   250.4 2503.11
#Mann= 3 ,-1,0
       0      .1       075.49358    .045       094.69195      .1       0
#XS Ineff= 1 ,-1
  163.77   244.4 2493.79
Permanent Ineff=
       F
Bank Sta=75.49358,94.69195
XS Rating Curve= 0 ,0
Exp/Cntr(USF)=0,0
Exp/Cntr=0.3,0.1

Type RM Length L Ch R = 1 ,6914    ,145.1,144.3,143
XS GIS Cut Line= 2
2271194.94480231488404.0932257992271184.42224263488675.575265413
#Sta/Elev= 30
       0 2522.45    13.1 2515.78    21.1 2512.55    37.1 2505.27    49.1 2498.64
    73.2 2489.12    77.1    2487    85.1 2478.27    89.2 2477.16    90.82477.107
   101.2 2476.62   109.72477.042   113.2 2477.33   117.2 2478.31   121.2 2478.81
   134.7 2479.33   149.2 2479.23   153.2 2480.25   173.2 2481.68   177.2 2482.43
   185.2 2482.25   193.2 2481.42   213.2 2480.13   221.3 2480.11   225.3  2480.7
   229.3 2482.06   241.3 2488.41   249.3 2492.91   253.3  2495.5   271.7 2505.57
#Mann= 3 ,-1,0
       0      .1       0    90.8    .045       0   109.7      .1       0
Bank Sta=90.8,109.7
XS Rating Curve= 0 ,0
Exp/Cntr(USF)=0,0
Exp/Cntr=0.3,0.1

Type RM Length L Ch R = 1 ,6770    ,114.6,116.3,117.7
XS GIS Cut Line= 2
2271043.60097366488401.8102399722271051.31329115488632.215724904
#Sta/Elev= 30
       0  2501.8    11.6    2496    19.4 2492.54    31.4  2488.6      36  2487.4
    51.4 2484.29    71.4 2482.16    75.4 2481.03    79.4  2478.5    83.4 2475.17
    87.4 2473.35    95.4  2473.6   102.3 2471.86   103.4 2471.53   107.4 2471.17
   111.4 2471.05   119.4  2471.7   123.4 2472.65   127.4 2474.06   131.4 2474.87
   143.4 2475.35   147.5  2475.1   162.6 2475.97   167.5 2475.98   179.5 2476.91
   195.5  2476.7   199.5 2477.65   203.5 2479.28   215.5 2486.07   230.5 2495.81
#Mann= 4 ,-1,0
       0      .1       0   102.3    .045       0   119.4      .1       0
     200     .06       0
Bank Sta=102.3,119.4
XS Rating Curve= 0 ,0
Exp/Cntr(USF)=0,0
Exp/Cntr=0.3,0.1

Type RM Length L Ch R = 1 ,6653    ,106.8,108.2,110.4
XS GIS Cut Line= 2
2270941.49096186488381.896345293 2270923.9533624488605.208445062
#Sta/Elev= 30
       0 2494.74    11.3 2491.96    19.3 2489.27    31.4 2483.77    43.4 2479.72
    55.5  2476.7    59.5 2475.93    71.5  2474.9    87.6 2474.19    95.6 2472.67
    99.6  2471.3   103.6 2469.26   104.7 2468.99   107.6  2468.4   112.2 2468.37
   123.3 2467.99   128.92468.586   130.8 2468.95   135.7 2470.56   147.7 2469.46
   159.8 2470.26   171.8 2469.19   183.8 2470.27   187.9 2471.34   195.9 2475.44
   199.9 2478.79   208.9 2488.65   211.9 2491.37     220 2497.51     224 2500.22
#Mann= 4 ,-1,0
       0      .1       0   112.2    .045       0   128.9      .1       0
     220     .06       0
Bank Sta=112.2,128.9
XS Rating Curve= 0 ,0
Exp/Cntr(USF)=0,0
Exp/Cntr=0.3,0.1

Type RM Length L Ch R = 1 ,6545    ,146.1,149.1,148.6
XS GIS Cut Line= 2
2270857.02652666488358.5267694292270807.25012339 488578.15849565
#Sta/Elev= 30
       0 2491.26    19.1 2485.58    27.3 2482.82    35.5 2480.59    39.6 2479.19
      56 2474.68    68.3 2472.04    76.5 2469.96    80.6 2469.36    94.3  2468.5
   105.3 2468.95   109.4 2468.83   125.8 2465.95   138.1 2464.91   142.2 2464.28
   150.4  2464.6   154.5 2465.41   158.6 2465.99   166.8 2465.25     175 2466.45
   179.1 2466.38   183.2 2465.66   187.3 2466.75   191.4 2470.41   195.5 2473.71
   203.5 2478.55   211.9 2482.81   216.9 2485.74   219.8 2487.15   225.2 2489.16
#Mann= 3 ,-1,0
       0      .1       0   138.1    .045       0   154.5      .1       0
Bank Sta=138.1,154.5
XS Rating Curve= 0 ,0
Exp/Cntr(USF)=0,0
Exp/Cntr=0.3,0.1

Type RM Length L Ch R = 1 ,6396    ,166.1,161,156.3
XS GIS Cut Line= 4
2270701.81043593488345.6519730792270711.16382231488400.603118048
2270667.90441031488532.7197006342270683.10366317488592.347538792
#Sta/Elev= 30
       0 2486.95    23.9 2479.57    44.2 2472.36    48.2 2470.55    56.3 2467.37
    64.8 2463.52      69 2462.48    85.8 2460.42    98.4 2460.85   102.6 2462.38
   106.9 2462.87   123.7 2462.23   136.3 2461.57   140.5 2460.44   144.7  2458.7
   148.9 2457.78   153.2 2457.38   157.4 2457.82   161.6 2458.66   165.8 2459.87
   169.5 2461.27   174.2 2462.15   189.6 2462.61   195.4 2463.62   211.7  2469.8
     225 2474.26   232.4 2477.46   244.8 2483.29   248.9 2485.48   256.3 2488.68
#Mann= 3 ,-1,0
       0      .1       0   144.7    .045       0   161.6      .1       0
Bank Sta=144.7,161.6
XS Rating Curve= 0 ,0
Exp/Cntr(USF)=0,0
Exp/Cntr=0.3,0.1

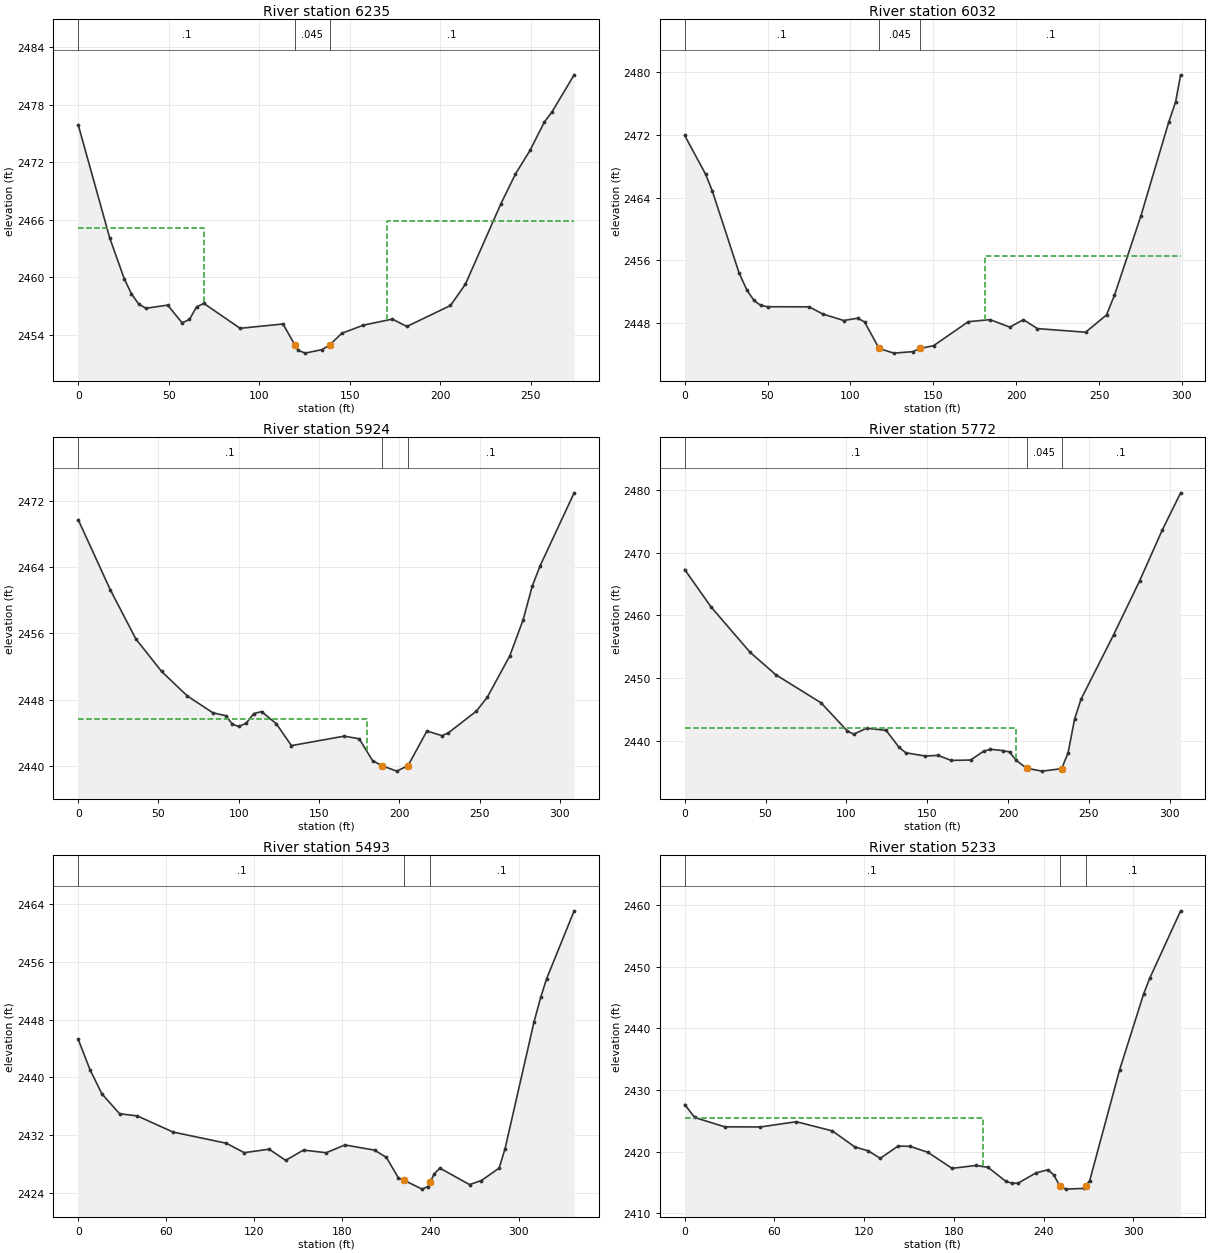
Type RM Length L Ch R = 1 ,6235    ,208.3,203.2,201
XS GIS Cut Line= 2
2270516.19324305488355.8232988512270526.77255374 488629.56296275
#Sta/Elev= 30
       0 2475.92    17.4 2464.12    25.4 2459.87    29.4 2458.29    33.4 2457.22
    37.4 2456.78    49.4 2457.11    57.4 2455.26    61.4 2455.61    65.4 2456.93
    69.4 2457.29    89.4 2454.69   113.1 2455.14  119.632452.966   121.4  2452.4
   125.4  2452.1   134.7 2452.47   138.8 2452.93   145.5 2454.16   157.5 2455.02
   173.5 2455.65   181.5 2454.88   205.6 2457.07   213.8 2459.28   233.5 2467.71
   241.5  2470.8   249.5 2473.25   257.5 2476.23   261.6 2477.25   273.9 2481.14
#Mann= 3 ,-1,0
       0      .1       0  119.63    .045       0   138.8      .1       0
#XS Ineff= 2 , 0
           69.57  2465.2  170.72         2465.93
Permanent Ineff=
       F       F
Bank Sta=119.63,138.8
XS Rating Curve= 0 ,0
Exp/Cntr(USF)=0,0
Exp/Cntr=0.3,0.1

Type RM Length L Ch R = 1 ,6032    ,114.7,108.4,106.3
XS GIS Cut Line= 2
2270283.44840805488361.112954192 2270368.0828935488648.076756444
#Sta/Elev= 30
       0  2471.9    12.6 2466.98    16.7 2464.82    32.8 2454.42    37.6  2452.2
    41.8 2450.92    45.9 2450.27    50.1 2450.11    75.1  2450.1    83.5 2449.17
      96 2448.36   104.3 2448.65   108.5 2448.19   117.3  2444.8   126.2 2444.21
   137.7  2444.4   141.9  2444.8   150.2 2445.16   171.1 2448.21   184.2 2448.47
   196.1 2447.52   204.4 2448.46   212.8 2447.33   241.9 2446.87   254.5 2449.07
   259.3 2451.58   275.3 2461.71     292 2473.58   296.2 2476.18   299.2 2479.61
#Mann= 3 ,0,0
       0      .1       0   117.3    .045       0   141.9      .1       0
#XS Ineff= 2 , 0
                          180.97         2456.54
Permanent Ineff=
       F       F
Bank Sta=117.3,141.9
XS Rating Curve= 0 ,0
Exp/Cntr(USF)=0,0
Exp/Cntr=0.3,0.1

Type RM Length L Ch R = 1 ,5924    ,143,152.1,162.2
XS GIS Cut Line= 3
2270184.56546851488365.3100987552270180.66822419488465.339369739
2270289.79106526488643.313527205
#Sta/Elev= 30
       0 2469.72    19.9 2461.29    35.9 2455.33    51.9 2451.41    67.9 2448.45
    83.9 2446.41    91.9 2446.06    95.9 2445.06    99.9 2444.76   104.6 2445.15
   109.3 2446.31   114.2 2446.56   123.4 2445.09   132.8 2442.45   165.6 2443.59
     175 2443.28   183.3 2440.65   189.1 2440.03   198.4 2439.37   205.42440.029
   217.2 2444.21   226.6 2443.65   230.5 2443.98     248 2446.61   254.8 2448.29
   268.8 2453.28   277.1 2457.63   282.8  2461.7   287.6 2464.11   308.9 2472.96
#Mann= 3 ,-1,0
       0      .1       0   189.1    .045       0   205.4      .1       0
#XS Ineff= 2 , 0
          180.16 2445.64
Permanent Ineff=
       F       F
Bank Sta=189.1,205.4
XS Rating Curve= 0 ,0
Exp/Cntr(USF)=0,0
Exp/Cntr=0.3,0.1

Type RM Length L Ch R = 1 ,5772    ,280,278.1,273.3
XS GIS Cut Line= 2
2270108.88978179488365.0801956982270081.11909125488670.557791643
#Sta/Elev= 30
       0  2467.3    16.2 2461.37    40.3 2454.14    56.3 2450.53    84.4 2446.03
   100.5 2441.58   104.5 2441.04   112.6    2442   124.6 2441.64   132.6 2438.94
   136.7 2438.08   148.7 2437.56   156.7 2437.66   164.8 2436.86   176.8 2436.92
   184.8 2438.31   188.9 2438.64   196.9 2438.42   200.9  2438.2   204.9  2436.9
   211.4 2435.61     221 2435.15   233.1 2435.54   237.1 2438.05   241.1 2443.42
   245.1 2446.62   265.2 2456.86   281.3 2465.47   295.3 2473.57   306.7 2479.53
#Mann= 3 ,0,0
       0      .1       0   211.4    .045       0   233.1      .1       0
#XS Ineff= 2 , 0
          205.03 2442.04
Permanent Ineff=
       F       F
Bank Sta=211.4,233.1
XS Rating Curve= 0 ,0
Exp/Cntr(USF)=0,0
Exp/Cntr=0.3,0.1

Type RM Length L Ch R = 1 ,5493    ,256.6,260.6,261.5
XS GIS Cut Line= 2
2269780.93115065488345.2439881692269828.53804872 488679.81468849
#Sta/Elev= 30
       0 2445.26       8 2441.06    16.1  2437.7    28.2 2434.93    40.3 2434.63
    64.6 2432.39   100.9 2430.84   113.1 2429.53   130.1 2430.01   141.3 2428.46
   153.5 2429.89     169 2429.52   181.7  2430.6   201.9 2429.88     210 2428.87
   218.1 2426.04   222.2 2425.68   234.3 2424.47   238.3 2424.83   239.8 2425.41
   242.4 2426.54   246.4 2427.39   266.6  2425.1   274.7 2425.66   286.8 2427.39
   290.8 2430.06   310.5 2447.63   315.1 2451.08   319.1 2453.65   337.9 2463.09
#Mann= 3 ,-1,0
       0      .1       0   222.2    .045       0   239.8      .1       0
Bank Sta=222.2,239.8
XS Rating Curve= 0 ,0
Exp/Cntr(USF)=0,0
Exp/Cntr=0.3,0.1

Type RM Length L Ch R = 1 ,5233    ,283.5,291,296.1
XS GIS Cut Line= 2
2269576.28352812488358.5171048122269561.59004106488689.936868464
#Sta/Elev= 30
       0 2427.63     6.7 2425.53    26.7 2424.01    50.7 2423.99    74.7 2424.84
    98.8 2423.34   113.8 2420.74   122.8  2420.1   130.8 2418.89   142.8 2420.89
   150.8 2420.84   162.8 2419.85   178.8 2417.27   194.9 2417.73   202.9 2417.43
   214.9 2415.14   218.9 2414.85   222.9 2414.84   234.9 2416.52   242.9 2417.03
   246.9  2416.2   250.9 2414.37   254.9 2413.89   266.9 2414.01   268.22414.412
   270.9 2415.28   290.9 2433.27     307 2445.62     311 2448.12   331.7 2459.09
#Mann= 3 ,-1,0
       0      .1       0   250.9    .045       0   268.2      .1       0
#XS Ineff= 2 , 0
          199.72 2425.43
Permanent Ineff=
       F       F
Bank Sta=250.9,268.2
XS Rating Curve= 0 ,0
Exp/Cntr(USF)=0,0
Exp/Cntr=0.3,0.1