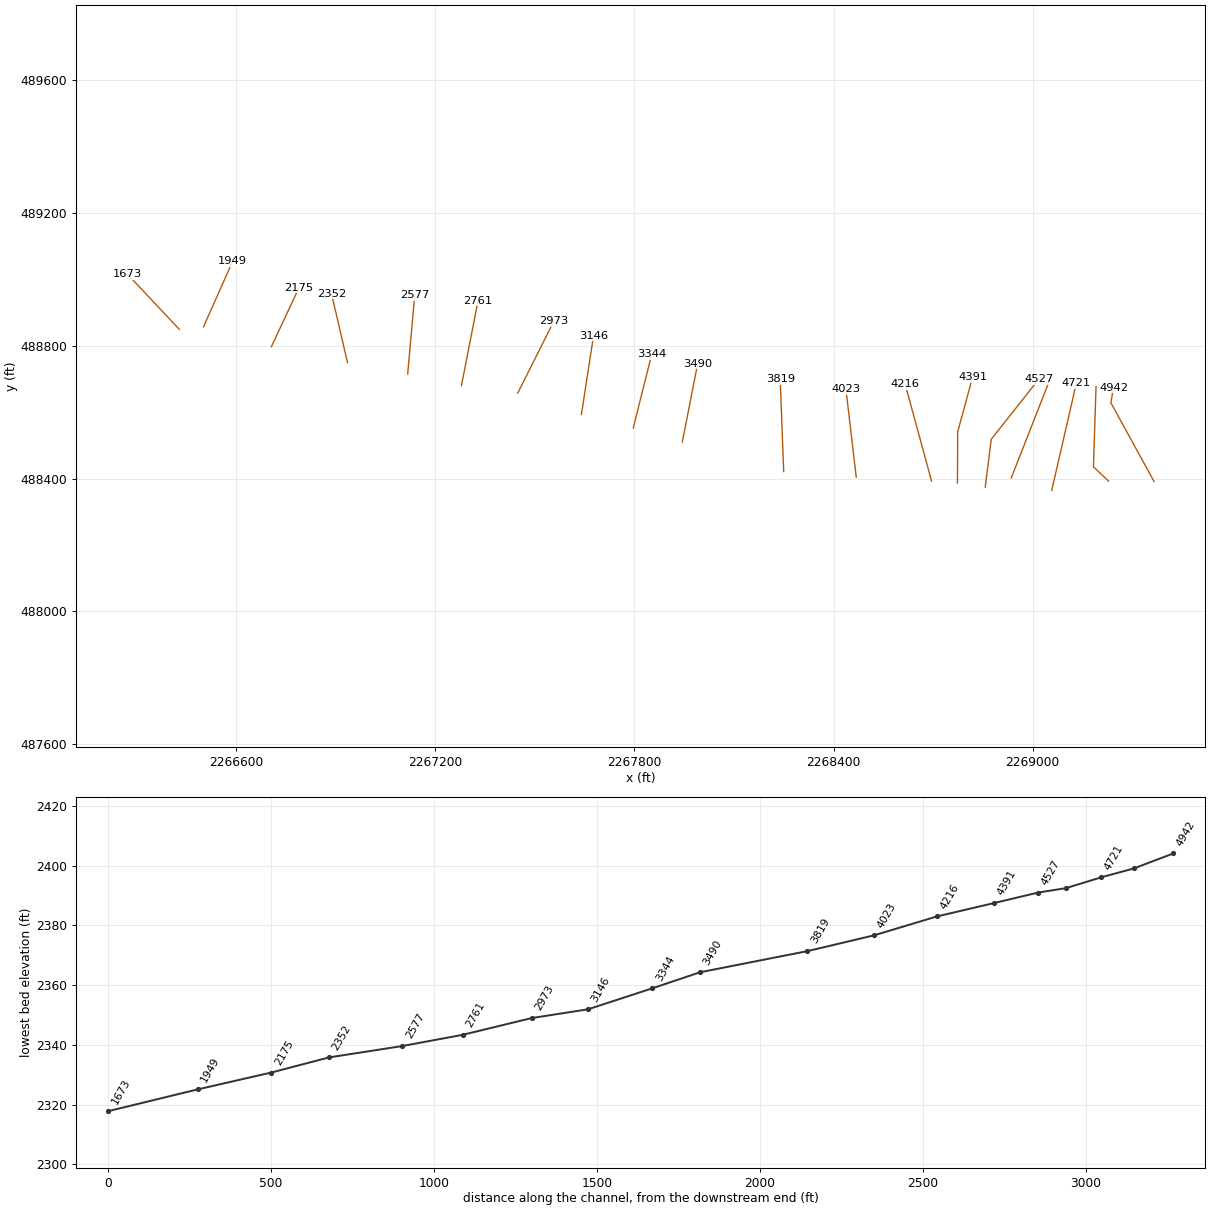
HEC-RAS study LAURELRN2.prj: LAURELRN2

--- LAURELRN2.g01 (geometry) --- (continued)

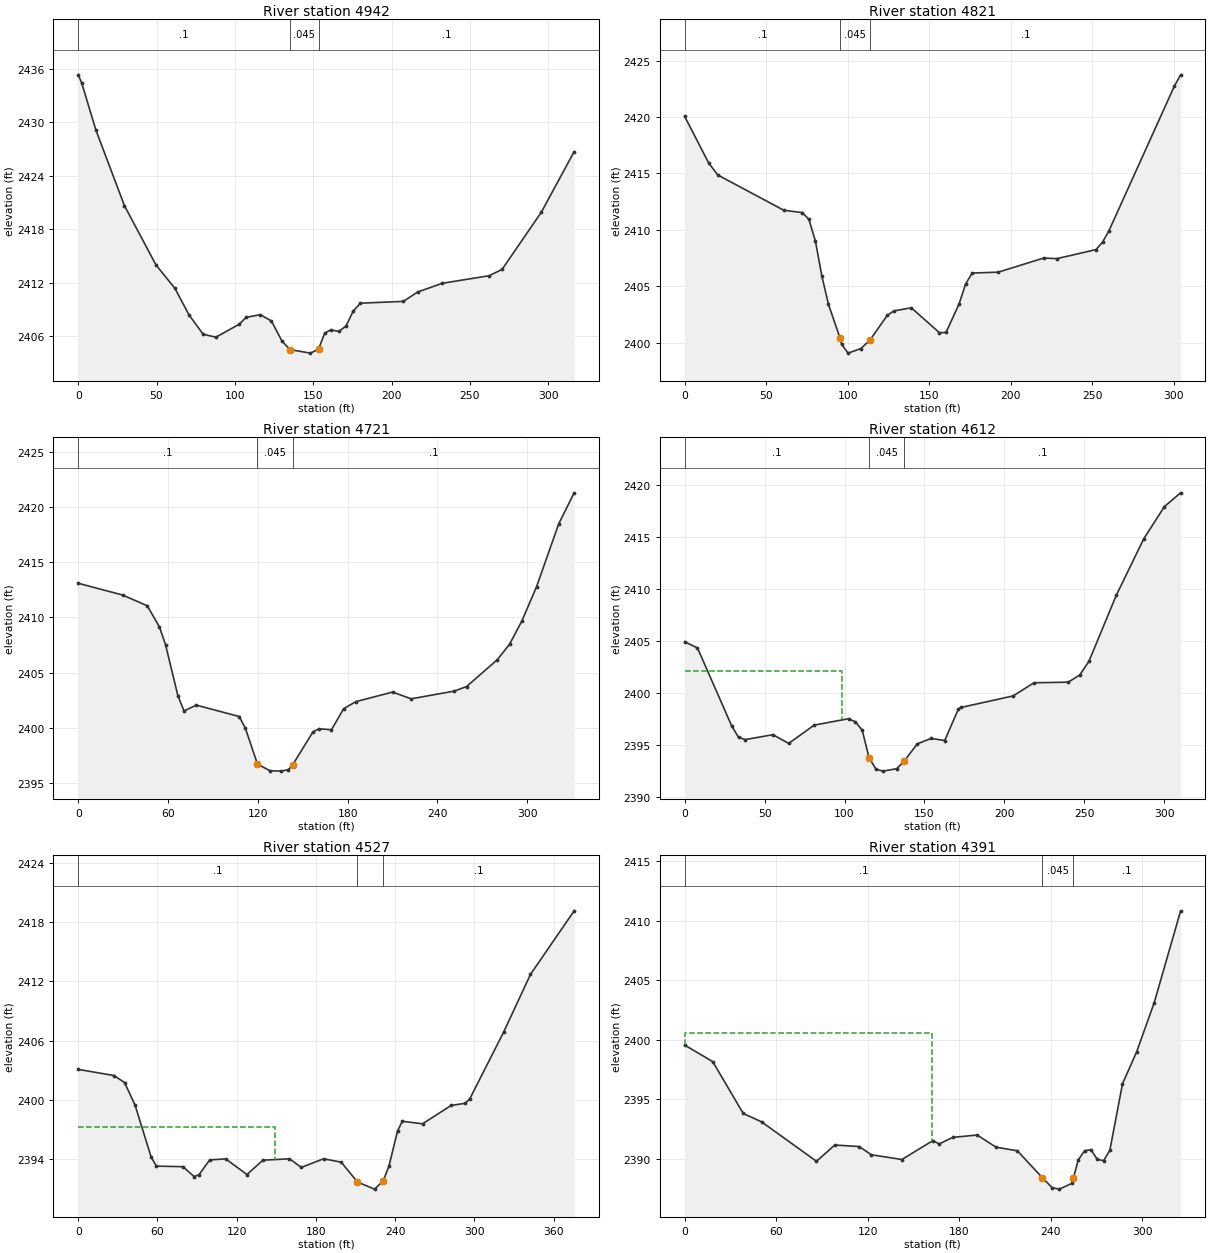
Type RM Length L Ch R = 1 ,4942    ,128.2,121.2,113
XS GIS Cut Line= 3
2269365.68361237488391.2808274532269235.53825477488628.434590186
2269243.25057226488673.744455424
#Sta/Elev= 30
       0 2435.33     2.2 2434.43    11.3 2429.12    29.5 2420.64    49.6 2413.99
    61.7 2411.36    70.6 2408.41    79.7  2406.2    87.9 2405.87   102.7 2407.32
   107.1 2408.09   116.2  2408.4   123.3 2407.69   129.9 2405.48   135.1 2404.48
   148.2 2404.08  153.362404.525   157.3 2406.33   161.1 2406.69   166.4 2406.52
     171 2407.15   175.5  2408.8   180.1 2409.69   207.5 2409.89   216.6 2410.94
   232.3 2411.92   262.2 2412.77   270.5 2413.48   295.6 2419.92   316.5  2426.7
#Mann= 3 ,-1,0
       0      .1       0   135.1    .045       0  153.36      .1       0
Bank Sta=135.1,153.36
XS Rating Curve= 0 ,0
Exp/Cntr(USF)=0,0
Exp/Cntr=0.3,0.1

Type RM Length L Ch R = 1 ,4821    ,102.1,99.6,96.2
XS GIS Cut Line= 3
2269228.44152767488392.5908090232269182.97367723488435.460496588
2269190.76816588 488677.08964468
#Sta/Elev= 30
       0 2420.05    14.8  2415.9    20.4 2414.85    60.8 2411.73    72.2 2411.52
    76.2 2410.92    80.2 2408.99    84.2 2405.86    88.2 2403.38   95.25 2400.42
    96.2 2399.87   100.2 2399.06     108 2399.46   113.62400.199   124.2  2402.4
   128.2  2402.8     139 2403.08   156.3 2400.87   160.3 2400.89   168.3 2403.42
   172.3 2405.18   176.3 2406.16   192.3 2406.24   220.2 2407.49   228.3 2407.44
   252.3 2408.24   256.3  2408.9   260.3 2409.93   300.3 2422.72   304.2 2423.74
#Mann= 3 ,-1,0
       0      .1       0   95.25    .045       0   113.6      .1       0
Bank Sta=95.25,113.6
XS Rating Curve= 0 ,0
Exp/Cntr(USF)=0,0
Exp/Cntr=0.3,0.1

Type RM Length L Ch R = 1 ,4721    ,111.1,109,106.3
XS GIS Cut Line= 2
2269057.19091288488364.2877162482269131.42196869488687.241011026
#Sta/Elev= 30
       0 2413.09    29.6 2412.03    46.1 2411.06    54.3 2409.14    58.4 2407.51
    66.6 2402.93    70.7 2401.54    78.9 2402.07   107.6 2401.04   111.7 2399.98
   119.8 2396.73   128.1 2396.14   135.8  2396.1   140.5 2396.24   143.4 2396.69
   156.9 2399.66     161 2399.93   169.2 2399.84   177.4 2401.75   185.6 2402.39
   210.1 2403.25   222.5 2402.64   251.3 2403.34   259.5 2403.75     280 2406.17
   288.2 2407.57   296.4 2409.66   306.3 2412.79   321.1 2418.47   331.4 2421.27
#Mann= 3 ,-1,0
       0      .1       0   119.8    .045       0   143.4      .1       0
Bank Sta=119.8,143.4
XS Rating Curve= 0 ,0
Exp/Cntr(USF)=0,0
Exp/Cntr=0.3,0.1

Type RM Length L Ch R = 1 ,4612    ,89.4,85.1,79.5
XS GIS Cut Line= 2
2268935.18958383488401.7722913462269048.59939366488690.558095759
#Sta/Elev= 30
       0 2404.91       8 2404.32    29.4 2396.81    33.7  2395.7      38 2395.49
    55.2 2395.96    65.1 2395.12      81 2396.88   102.5  2397.5   106.8  2397.2
   111.1 2396.38   115.4 2393.72   119.7 2392.64     124 2392.45   132.6 2392.68
   137.42393.425   145.5 2395.07   154.1  2395.6   162.7  2395.4   171.3 2398.45
   173.1 2398.59   205.6  2399.7   218.5 2400.96     240 2401.02   247.2 2401.71
   252.9 2403.02   270.1 2409.41   287.3 2414.85   300.2 2417.94   310.3 2419.26
#Mann= 3 ,-1,0
       0      .1       0   115.4    .045       0   137.4      .1       0
#XS Ineff= 2 , 0
           98.29 2402.14
Permanent Ineff=
       F       F
Bank Sta=115.4,137.4
XS Rating Curve= 0 ,0
Exp/Cntr(USF)=0,0
Exp/Cntr=0.3,0.1

Type RM Length L Ch R = 1 ,4527    ,130.2,135.9,142.2
XS GIS Cut Line= 3
2268856.90423545488374.4036688442268875.09137563488518.601708835
2269017.99033418488699.174029183
#Sta/Elev= 30
       0  2403.1      27 2402.48    35.1 2401.77    43.1 2399.47    55.2 2394.24
    59.2 2393.31    79.4 2393.25    87.8 2392.25    91.5 2392.44    99.6 2393.94
   111.7 2394.04   127.8 2392.46   139.9 2393.91     160 2394.05     169 2393.18
   185.8 2394.05   199.2 2393.71   211.5  2391.7   224.4 2390.98   230.9 2391.79
   235.3 2393.29   241.9 2396.89   245.5 2397.85   260.8 2397.59   282.4 2399.45
   293.2 2399.67   296.6 2400.13   322.1 2406.85   342.5 2412.71   375.6 2419.15
#Mann= 3 ,-1,0
       0      .1       0   211.5    .045       0   230.9      .1       0
#XS Ineff= 2 , 0
          148.85 2397.24
Permanent Ineff=
       F       F
Bank Sta=211.5,230.9
XS Rating Curve= 0 ,0
Exp/Cntr(USF)=0,0
Exp/Cntr=0.3,0.1

Type RM Length L Ch R = 1 ,4391    ,165.3,174.8,181.7
XS GIS Cut Line= 3
2268773.16318407 488386.823839242268773.86596901488540.733739135
2268818.84420459488705.888197926
#Sta/Elev= 30
       0 2399.56    18.4 2398.17    38.4 2393.81    50.4 2393.11    86.4 2389.79
    98.4 2391.16   114.4 2391.03   122.4 2390.34   142.4 2389.94   162.7 2391.53
   166.8 2391.25   175.7  2391.8   191.7    2392   204.1 2390.98   218.1 2390.67
   234.4 2388.42   240.9 2387.57   245.6 2387.45   253.9 2387.94  254.882388.414
     258 2389.91   262.2 2390.68   266.3 2390.77   270.5 2389.95   274.6 2389.84
   278.7 2390.71     287 2396.31   296.3    2399   307.8 2403.13   325.1 2410.85
#Mann= 3 ,-1,0
       0      .1       0   234.4    .045       0  254.88      .1       0
#XS Ineff= 2 , 0
          162.32 2400.55
Permanent Ineff=
       F       F
Bank Sta=234.4,254.88
XS Rating Curve= 0 ,0
Exp/Cntr(USF)=0,0
Exp/Cntr=0.3,0.1

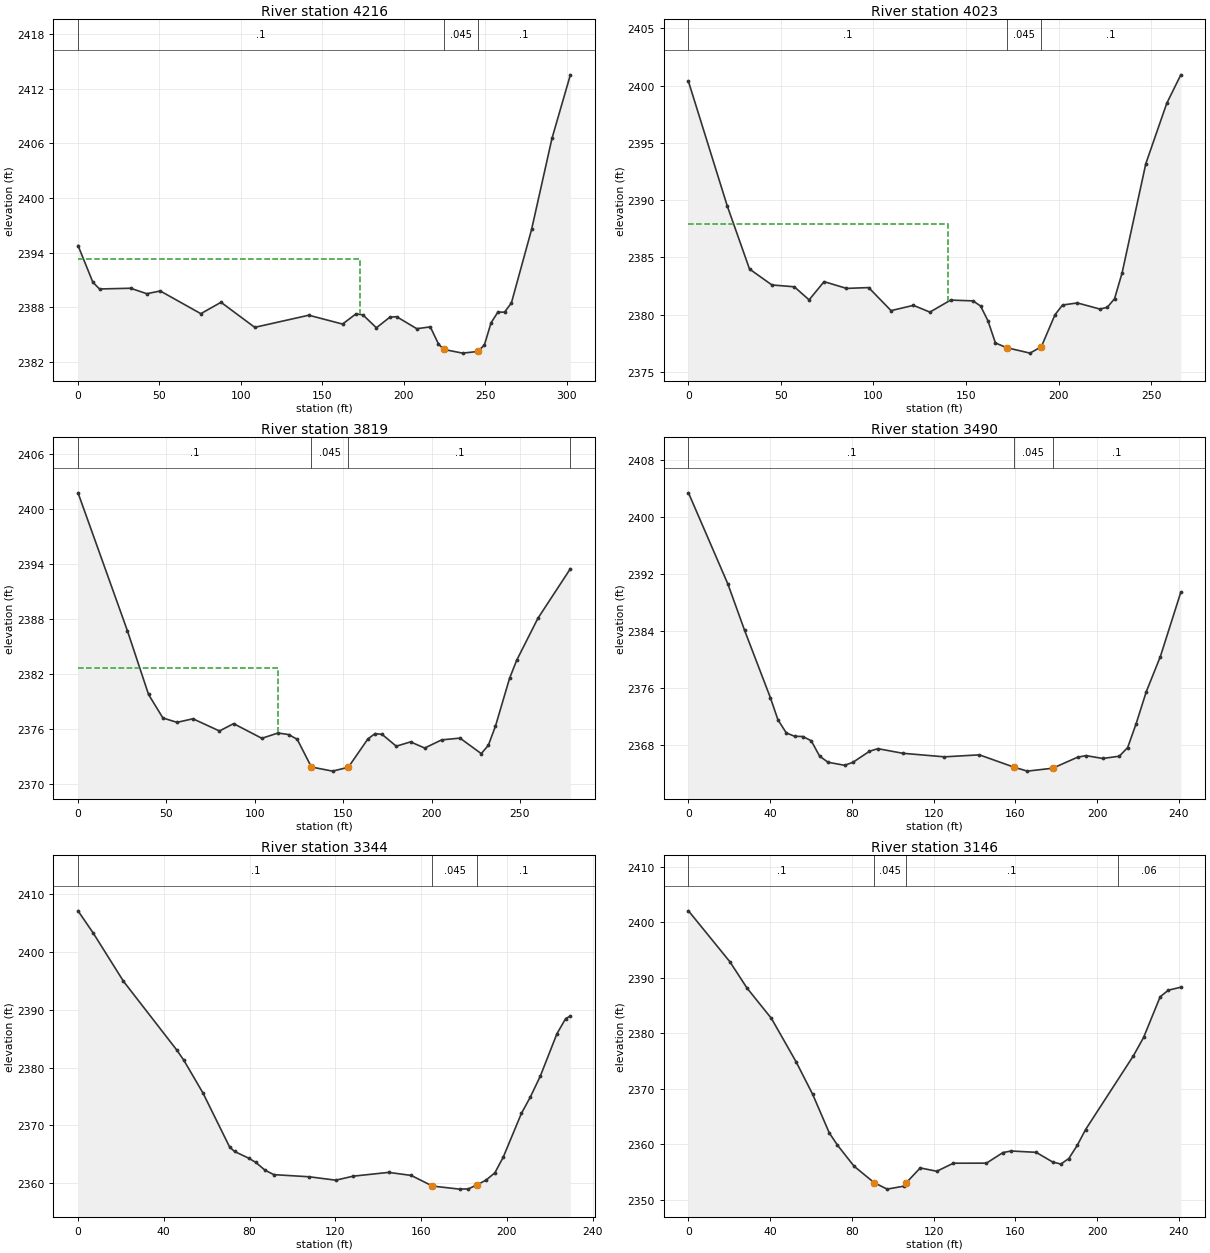
Type RM Length L Ch R = 1 ,4216    ,195.1,193.1,190.5
XS GIS Cut Line= 2
2268695.15405673488392.4461186882268615.73935952488684.101865064
#Sta/Elev= 30
       0 2394.79     9.1 2390.76    13.2 2390.02    32.3  2390.1    42.2  2389.5
    50.5  2389.8    75.4 2387.31    87.8 2388.56   108.5 2385.81   141.7 2387.14
   162.4 2386.17   170.7 2387.29   174.9 2387.18   183.2 2385.76   191.5 2386.93
   195.6 2386.98     208 2385.66   216.3 2385.86   221.3 2383.99   224.5 2383.39
   236.1 2382.98   245.4 2383.16   249.5 2383.86   253.6 2386.31   257.8 2387.48
   261.9 2387.48   266.1 2388.49   278.5 2396.56     291 2406.54   302.3 2413.52
#Mann= 3 ,-1,0
       0      .1       0   224.5    .045       0   245.4      .1       0
#XS Ineff= 2 , 0
          173.07 2393.28
Permanent Ineff=
       F       F
Bank Sta=224.5,245.4
XS Rating Curve= 0 ,0
Exp/Cntr(USF)=0,0
Exp/Cntr=0.3,0.1

Type RM Length L Ch R = 1 ,4023    ,205.5,204.3,202.8
XS GIS Cut Line= 2
2268468.15452401488404.3934625162268437.23198704488668.640596581
#Sta/Elev= 30
       0 2400.36    20.9 2389.53      33 2383.99    45.1  2382.6    57.2 2382.44
    65.2  2381.3    73.3 2382.89    85.4  2382.3    97.4 2382.37   109.5 2380.36
   121.6 2380.82   130.5 2380.23   141.7 2381.28   153.8 2381.21   157.9 2380.76
   161.9 2379.46   165.9 2377.54   171.9 2377.13   184.6 2376.65  190.732377.208
   198.1    2380   202.2 2380.85   210.2 2381.03   222.3  2380.5   226.3 2380.64
   230.3  2381.4   234.4 2383.67   247.2 2393.19   258.5 2398.45   266.1 2400.94
#Mann= 3 ,-1,0
       0      .1       0   171.9    .045       0  190.73      .1       0
#XS Ineff= 2 , 0
          140.52 2387.89
Permanent Ineff=
       F       F
Bank Sta=171.9,190.73
XS Rating Curve= 0 ,0
Exp/Cntr(USF)=0,0
Exp/Cntr=0.3,0.1

Type RM Length L Ch R = 1 ,3819    ,332.6,329,322
XS GIS Cut Line= 2
2268249.58841046 488421.260300862268239.04663649488699.563133547
#Sta/Elev= 30
       0 2401.73    27.9  2386.7    39.9 2379.73      48 2377.17      56 2376.69
      65 2377.08      80 2375.75      88 2376.55     104 2374.95   113.1 2375.53
   119.1 2375.36     124 2374.84     132 2371.82     144 2371.37  152.88 2371.79
     164 2374.89     168 2375.46     172 2375.38     180 2374.09   188.1 2374.56
   196.1 2373.89   205.7 2374.78   216.1 2374.97   228.1 2373.28   232.1 2374.19
   236.1 2376.26   244.1 2381.49   248.1 2383.45   260.1 2388.03   278.5 2393.45
#Mann= 4 ,-1,0
       0      .1       0     132    .045       0  152.88      .1       0
   278.5     .06       0
#XS Ineff= 2 , 0
          113.14 2382.66
Permanent Ineff=
       F       F
Bank Sta=132,152.88
XS Rating Curve= 0 ,0
Exp/Cntr(USF)=0,0
Exp/Cntr=0.3,0.1

Type RM Length L Ch R = 1 ,3490    ,146.5,146.1,144.9
XS GIS Cut Line= 2
2267944.08463554488510.1929618852267990.45045932488746.739571873
#Sta/Elev= 30
       0 2403.44    19.3 2390.61    27.5 2384.08    40.1 2374.63    43.8 2371.52
    47.9 2369.67      52  2369.2      56 2369.17    60.1 2368.57    64.2 2366.41
    68.3 2365.55    76.4 2365.12    80.5 2365.54    88.6 2367.09    92.7 2367.46
   104.9 2366.81   125.3 2366.31   142.4 2366.59   159.4 2364.85   165.9  2364.3
   178.3 2364.71   190.5 2366.26   194.6 2366.48   202.8 2366.08   210.9  2366.4
     215 2367.62   219.1 2370.94   224.1 2375.47     231 2380.42     241 2389.46
#Mann= 3 ,-1,0
       0      .1       0   159.4    .045       0   178.3      .1       0
Bank Sta=159.4,178.3
XS Rating Curve= 0 ,0
Exp/Cntr(USF)=0,0
Exp/Cntr=0.3,0.1

Type RM Length L Ch R = 1 ,3344    ,195.9,197.4,200.6
XS GIS Cut Line= 2
2267796.18030135488552.6107080652267852.09460313488775.303875509
#Sta/Elev= 30
       0 2407.16     7.1  2403.3    21.2 2394.95      46 2383.07    49.3  2381.3
    58.3 2375.58    70.7 2366.24      73 2365.47    79.6 2364.31    82.9 2363.58
    87.2 2362.23    91.3 2361.46   107.8 2361.09   120.2  2360.5   128.4  2361.2
   144.9 2361.85   155.4 2361.32   165.3 2359.48   177.9 2358.95     182 2358.99
   186.2 2359.71   190.3 2360.52   194.4 2361.78   198.3  2364.5   206.8 2372.09
   210.9 2374.88   215.6 2378.54   223.3 2385.84   227.4  2388.5   229.6 2388.93
#Mann= 3 ,-1,0
       0      .1       0   165.3    .045       0   186.2      .1       0
Bank Sta=165.3,186.2
XS Rating Curve= 0 ,0
Exp/Cntr(USF)=0,0
Exp/Cntr=0.3,0.1

Type RM Length L Ch R = 1 ,3146    ,176.1,173,168.9
XS GIS Cut Line= 2
2267640.00587223488593.1003748732267676.63938029488831.218177292
#Sta/Elev= 30
       0 2402.05    20.3 2392.86    28.6 2388.16    40.6 2382.66    52.7 2374.83
    60.8 2368.97    68.9 2362.04    72.9 2359.84      81 2356.05    90.8 2353.09
    97.2 2351.91   105.3 2352.44  106.652353.086   113.4 2355.73   121.5 2355.13
   129.6 2356.58   145.8 2356.59   153.9  2358.5   157.9 2358.78   170.1 2358.54
   178.2  2356.8   182.2 2356.43   186.1 2357.42   190.3 2359.84   194.3 2362.64
   217.7 2375.93   222.7 2379.24   230.8 2386.56   234.8 2387.75   240.9 2388.29
#Mann= 4 ,-1,0
       0      .1       0    90.8    .045       0  106.65      .1       0
     210     .06       0
Bank Sta=90.8,106.65
XS Rating Curve= 0 ,0
Exp/Cntr(USF)=0,0
Exp/Cntr=0.3,0.1

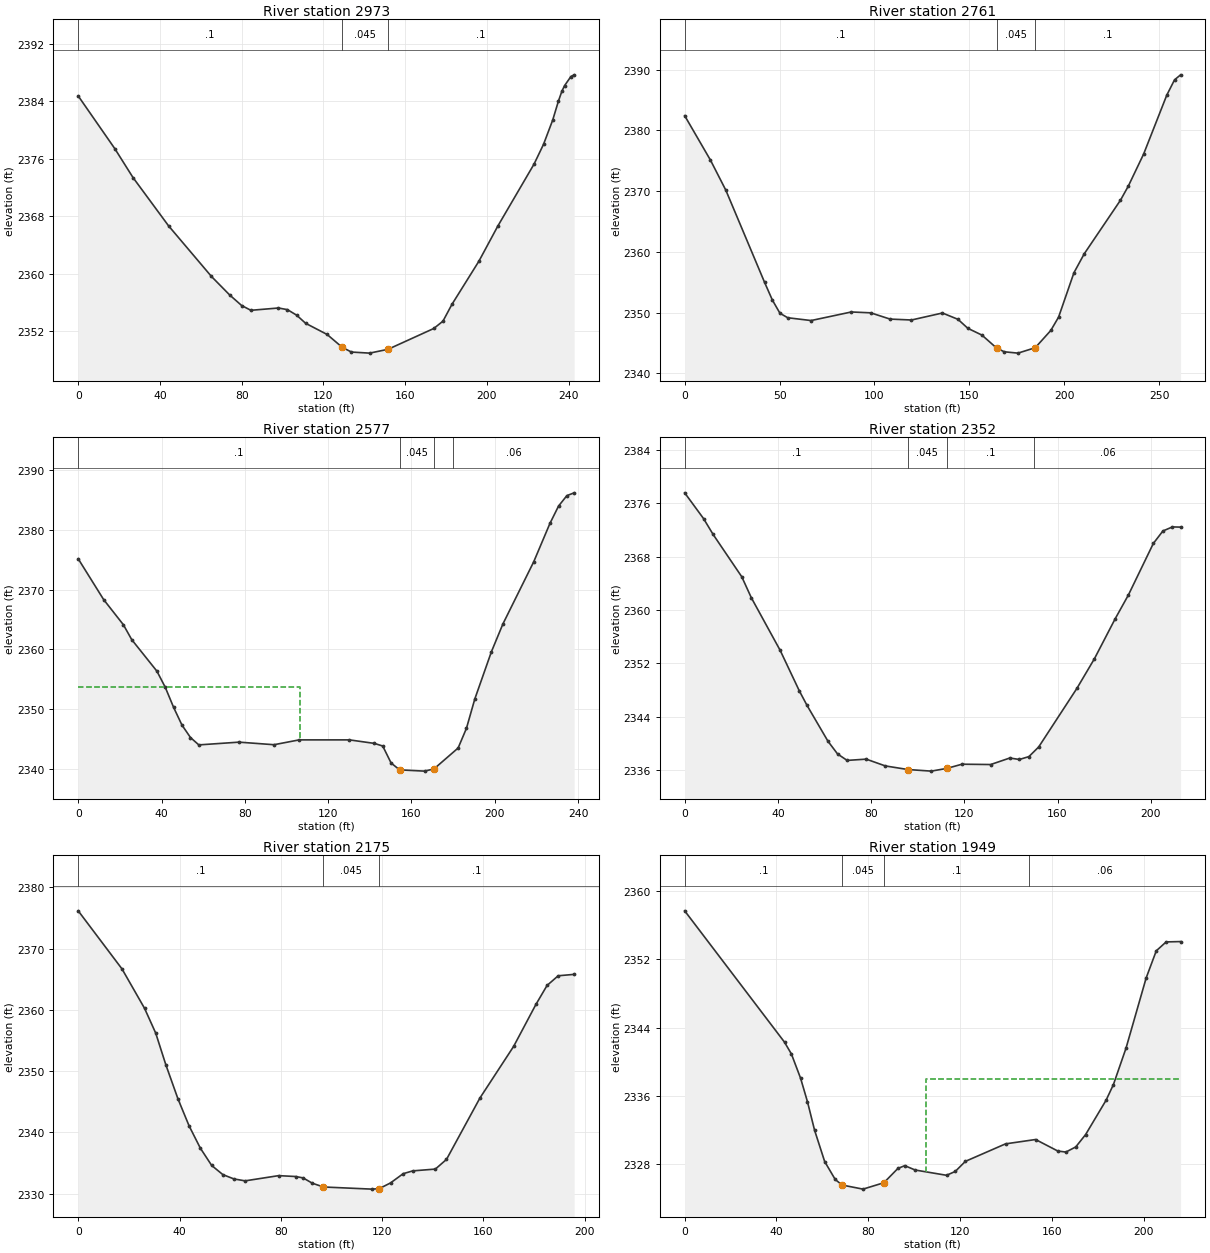
Type RM Length L Ch R = 1 ,2973    ,207.2,212.3,215.8
XS GIS Cut Line= 2
2267448.16197473488657.6910338292267557.09845924488874.599963158
#Sta/Elev= 30
       0 2384.76    17.9 2377.43    26.8 2373.41    44.2 2366.69    65.2 2359.64
    74.1 2357.07      80 2355.59    84.5 2354.93      98 2355.25   102.4 2355.02
   106.9 2354.25   111.3 2353.12   121.8 2351.57   129.2 2349.78   133.7 2349.12
   142.6 2348.97   151.6  2349.5     174  2352.4   178.5 2353.42   182.9 2355.76
   196.1 2361.77   205.3 2366.63   223.1 2375.29   227.7 2378.02   232.2  2381.4
     235 2384.04   236.7 2385.42     238 2386.19   241.1 2387.46   242.7  2387.7
#Mann= 3 ,-1,0
       0      .1       0   129.2    .045       0   151.6      .1       0
Bank Sta=129.2,151.6
XS Rating Curve= 0 ,0
Exp/Cntr(USF)=0,0
Exp/Cntr=0.3,0.1

Type RM Length L Ch R = 1 ,2761    ,182.4,184.5,185.5
XS GIS Cut Line= 2
2267278.49099001488679.8639466052267328.62105368488936.298503056
#Sta/Elev= 30
       0 2382.41    13.6 2375.09    21.7 2370.14    42.1 2354.99    46.2 2352.08
    50.2 2349.91    54.3 2349.17    66.6 2348.71    87.8 2350.12      98 2349.98
   108.2 2348.95   119.5  2348.8   135.8 2349.95     144 2348.91   149.2 2347.43
   156.6 2346.32   164.4 2344.17   168.4 2343.57   175.6 2343.35   184.7 2344.24
   192.9 2347.08     197 2349.27   205.1 2356.58   210.5 2359.68   229.6  2368.5
   233.7  2370.8   241.8 2376.09     254 2385.78   258.1 2388.31   261.3 2389.13
#Mann= 3 ,-1,0
       0      .1       0   164.4    .045       0   184.7      .1       0
Bank Sta=164.4,184.7
XS Rating Curve= 0 ,0
Exp/Cntr(USF)=0,0
Exp/Cntr=0.3,0.1

Type RM Length L Ch R = 1 ,2577    ,220.7,224.8,229.1
XS GIS Cut Line= 2
2267116.53232278488715.5334149832267137.74119587488952.687177716
#Sta/Elev= 30
       0 2375.14    12.2 2368.32    21.7  2364.1    25.7 2361.61    37.8 2356.33
    41.8 2353.63    45.8 2350.28    49.8 2347.32    53.9 2345.23    57.9    2344
    77.2 2344.46      94 2344.03   106.1 2344.84   130.2 2344.84   142.2 2344.25
   146.2 2343.81   150.2 2340.98   154.3 2339.82   166.3 2339.61   170.8 2339.98
   182.4 2343.48   186.4 2346.78   190.4 2351.68   198.4 2359.61   203.9 2364.24
   218.7 2374.65   226.5 2381.08   230.6 2383.96   234.6 2385.71   238.1 2386.18
#Mann= 4 ,-1,0
       0      .1       0   154.3    .045       0   170.8      .1       0
     180     .06       0
#XS Ineff= 2 , 0
          106.68 2353.76
Permanent Ineff=
       F       F
Bank Sta=154.3,170.8
XS Rating Curve= 0 ,0
Exp/Cntr(USF)=0,0
Exp/Cntr=0.3,0.1

Type RM Length L Ch R = 1 ,2352    ,184.7,177.2,166.4
XS GIS Cut Line= 2
2266935.29286183 488749.274803992266887.09087753 488956.54333646
#Sta/Elev= 30
       0  2377.6     8.1 2373.73    12.2 2371.35    24.5 2364.99    28.6 2361.84
      41 2353.92    49.2 2347.85    52.5 2345.67    61.5 2340.28    65.6 2338.38
    69.7 2337.41    77.9  2337.6    86.1 2336.58    95.8 2336.04   105.8  2335.8
   112.5 2336.21     119 2336.84   131.3 2336.79   139.5 2337.77   143.6 2337.55
   147.7 2337.98   151.9 2339.43   168.3 2348.23   175.8 2352.67   184.7 2358.67
   190.4 2362.26   201.1    2370   205.2 2371.87   209.3 2372.48   212.8 2372.45
#Mann= 4 ,-1,0
       0      .1       0    95.8    .045       0   112.5      .1       0
     150     .06       0
Bank Sta=95.8,112.5
XS Rating Curve= 0 ,0
Exp/Cntr(USF)=0,0
Exp/Cntr=0.3,0.1

Type RM Length L Ch R = 1 ,2175    ,224.1,225.7,226.1
XS GIS Cut Line= 2
2266705.85141658488797.4767882852266788.75882957488974.860090492
#Sta/Elev= 30
       0 2376.16    17.3 2366.67    26.2 2360.24    30.6  2356.2    34.6 2351.03
    39.4 2345.45    43.8 2341.04    48.2 2337.44    52.7  2334.6    57.1 2333.11
    61.5  2332.4    65.9 2332.09    79.1 2332.94    85.8  2332.8    88.8 2332.57
    92.4 2331.71    96.8 2331.09   115.9 2330.74   118.8 2330.81   123.3 2331.75
   128.3 2333.26   132.1 2333.72     141 2334.01   145.4 2335.59   158.6 2345.61
   171.9 2354.03   180.7 2360.88   185.1 2363.98   189.5 2365.56   195.8 2365.79
#Mann= 3 ,-1,0
       0      .1       0    96.8    .045       0   118.8      .1       0
Bank Sta=96.8,118.8
XS Rating Curve= 0 ,0
Exp/Cntr(USF)=0,0
Exp/Cntr=0.3,0.1

Type RM Length L Ch R = 1 ,1949    ,250.3,275.8,288.2
XS GIS Cut Line= 2
2266501.26978167488857.4594995542266589.11789804489054.942065172
#Sta/Elev= 30
       0 2357.69    43.5 2342.31    46.5 2340.93    50.5 2338.09    53.5 2335.34
    56.6    2332      61 2328.33    65.6 2326.23    68.6 2325.58    77.7  2325.1
    86.8 2325.85    92.9 2327.52    95.9 2327.85   100.4 2327.34   114.1 2326.72
   117.9 2327.17   122.3 2328.35   139.8  2330.4   152.9 2330.91   162.6 2329.56
   166.1 2329.44   170.4 2330.04   174.7 2331.49   183.6  2335.5   186.8 2337.33
   192.3  2341.6   201.1 2349.84   205.5 2353.01   209.8 2354.05   216.1 2354.09
#Mann= 4 ,-1,0
       0      .1       0    68.6    .045       0    86.8      .1       0
     150     .06       0
#XS Ineff= 2 , 0
                          105.07         2338.02
Permanent Ineff=
       F       F
Bank Sta=68.6,86.8
XS Rating Curve= 0 ,0
Exp/Cntr(USF)=0,0
Exp/Cntr=0.3,0.1

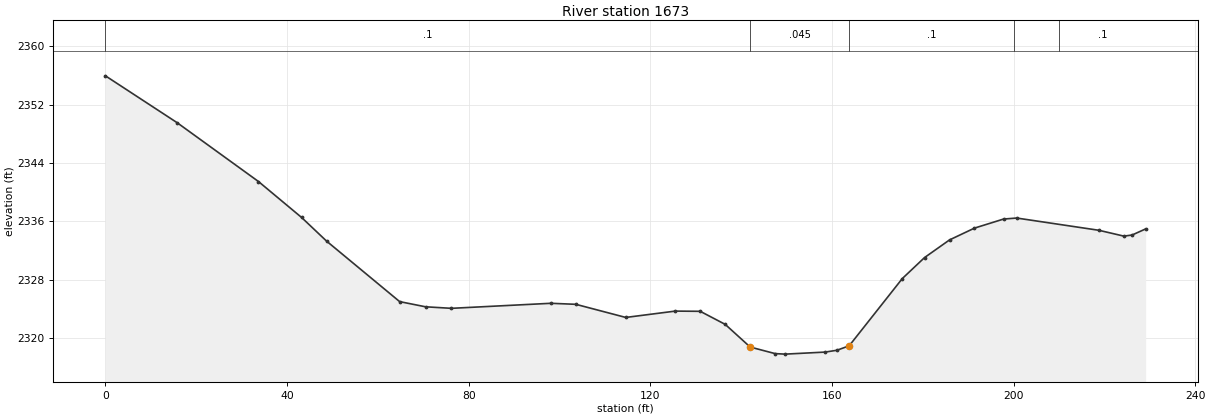
Type RM Length L Ch R = 1 ,1673    ,162.9,155.7,148.1
XS GIS Cut Line= 2
2266428.34651317488849.6857534582266271.48491656 489016.66745307
#Sta/Elev= 30
       0 2355.94    15.8 2349.51    33.7 2341.45    43.2 2336.52    48.7 2333.28
    64.8 2324.98    70.5 2324.27    76.2 2324.06    98.1 2324.75   103.6 2324.61
   114.6 2322.81   125.5 2323.68     131 2323.65   136.5 2321.86     142 2318.75
   147.5 2317.85   149.7 2317.78   158.5 2318.06   161.1 2318.31   163.8 2318.92
   175.5 2328.14   180.4 2331.02   185.9 2333.44   191.4 2335.06   197.8  2336.3
   200.7 2336.44   218.8 2334.76   224.3 2333.96   226.1 2334.11   229.1 2334.95
#Mann= 5 ,-1,0
       0      .1       0     142    .045       0   163.8      .1       0
     200     .06       0     210      .1       0
Bank Sta=142,163.8
XS Rating Curve= 0 ,0
Exp/Cntr(USF)=0,0
Exp/Cntr=0.3,0.1