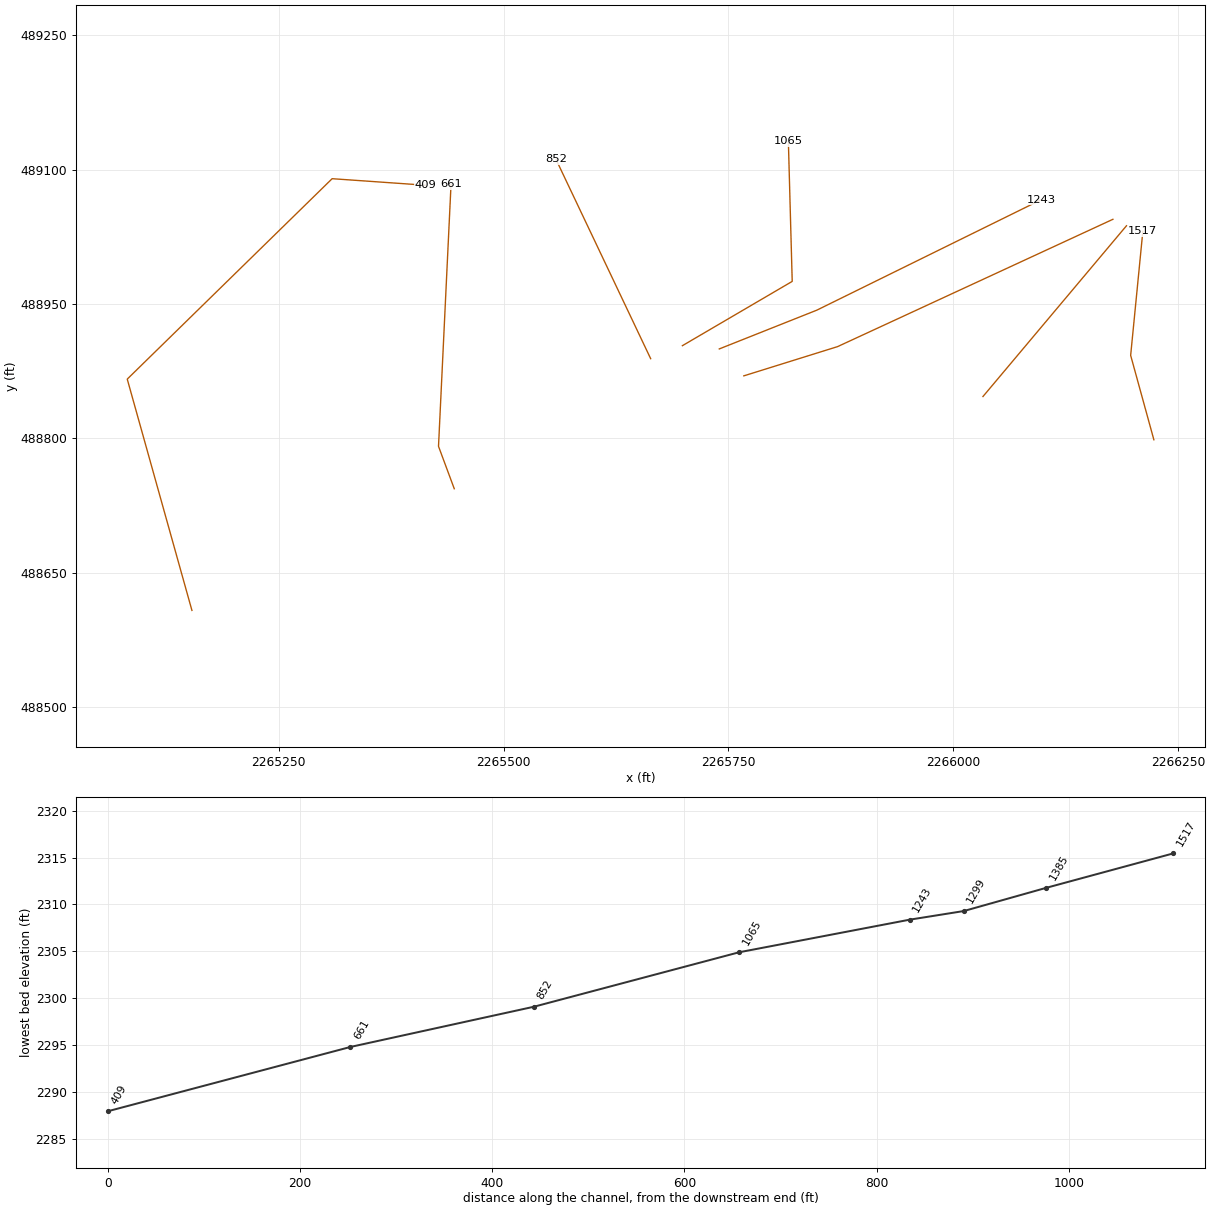
HEC-RAS study LAURELRN2.prj: LAURELRN2

--- LAURELRN2.g01 (geometry) --- (continued)

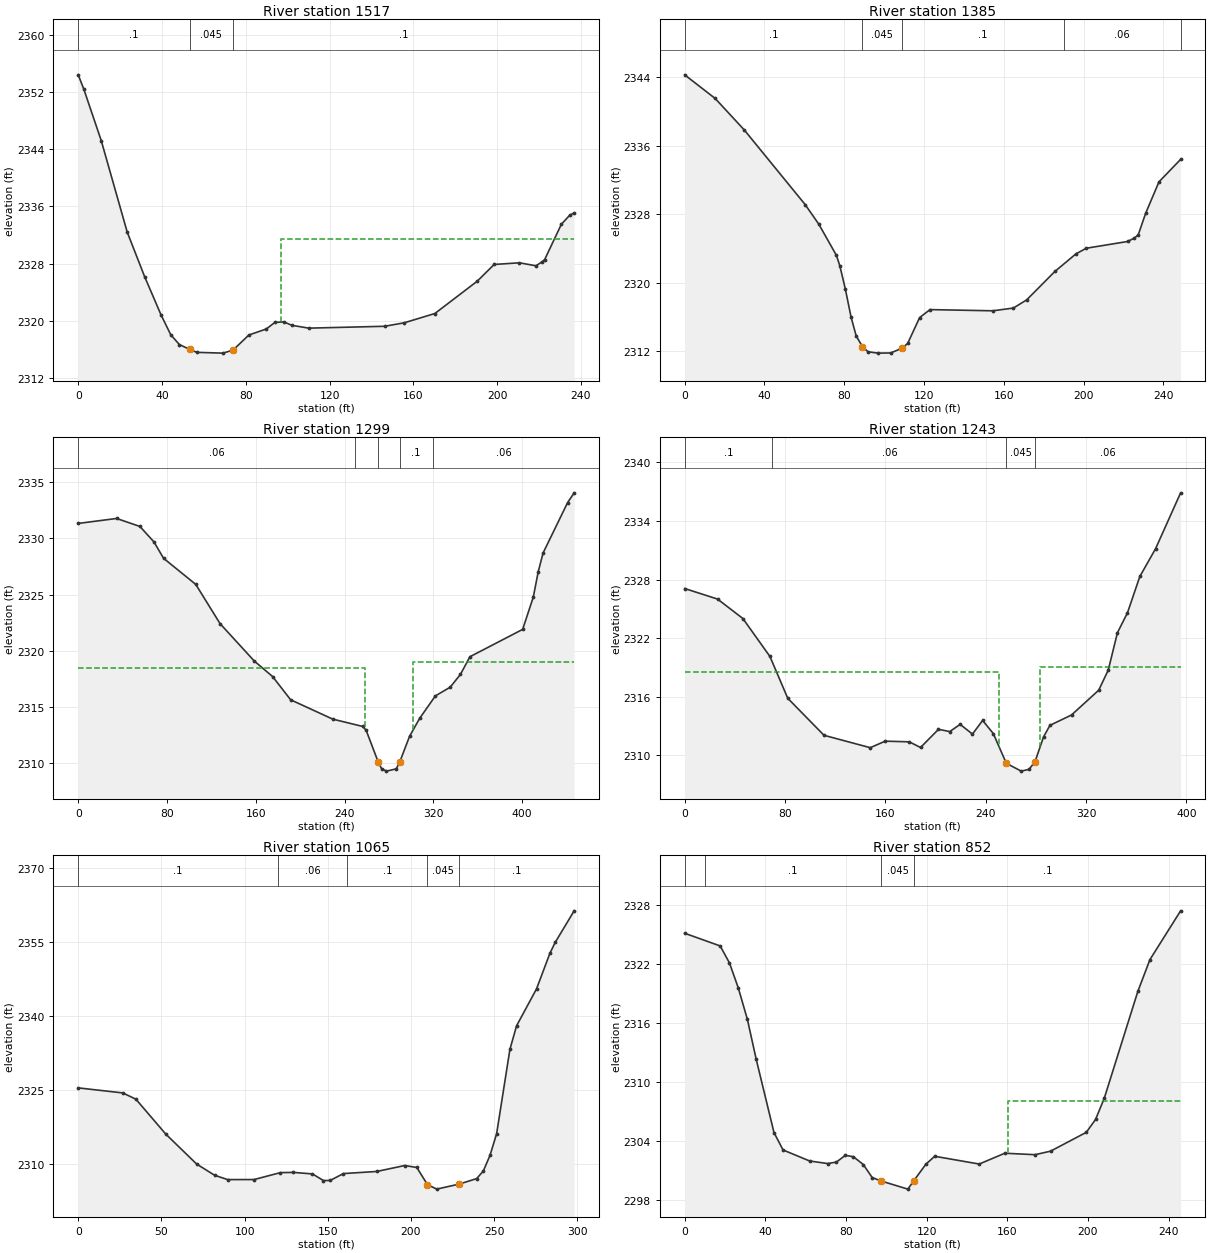
Type RM Length L Ch R = 1 ,1517    ,145.9,132.1,116.4
XS GIS Cut Line= 3
2266223.03492342488798.579233274 2266197.2216329488892.787553278
2266210.76429852489031.215101142
#Sta/Elev= 30
       0 2354.43     2.7  2352.4      11 2345.21    23.4  2332.4    31.7 2326.17
    39.6 2320.77    44.2 2318.02    48.3 2316.65    53.3 2315.97    56.6 2315.56
    69.1 2315.45    73.9 2315.87    81.5 2317.99    89.8 2318.83    93.9 2319.75
    98.1 2319.83   102.1 2319.34   110.1 2318.95   146.3 2319.21   155.7  2319.7
   170.3    2321   190.5 2325.52   198.6 2327.87   210.7  2328.1   218.6 2327.68
   221.6 2328.27   222.7 2328.54   230.7  2333.5   234.7 2334.77   236.8 2335.08
#Mann= 3 ,-1,0
       0      .1       0    53.3    .045       0    73.9      .1       0
#XS Ineff= 2 , 0
                           96.79         2331.48
Permanent Ineff=
       F       F
Bank Sta=53.3,73.9
XS Rating Curve= 0 ,0
Exp/Cntr(USF)=0,0
Exp/Cntr=0.3,0.1

Type RM Length L Ch R = 1 ,1385    ,93.8,85.9,80.9
XS GIS Cut Line= 2
2266032.98792215488846.8398958682266192.59004792489037.505522636
#Sta/Elev= 30
       0 2344.26    15.3  2341.5    29.9 2337.82    60.4 2329.12    67.3 2326.81
    76.1 2323.18    77.8 2321.96    80.6 2319.21    83.4 2316.01      86 2313.78
    89.1 2312.55    91.9 2311.94    96.9 2311.78   103.3  2311.8     109 2312.36
   111.8 2312.91   117.8 2315.93     123 2316.86   154.5 2316.72   164.8 2317.04
   171.5    2318   185.6 2321.31   196.1 2323.35   201.3 2324.02   222.1 2324.81
   225.4  2325.2   227.4 2325.58   231.1 2328.09   237.8 2331.77   248.6 2334.38
#Mann= 5 ,-1,0
       0      .1       0    89.1    .045       0     109      .1       0
     190     .06       0  248.65      .1       0
Bank Sta=89.1,109
XS Rating Curve= 0 ,0
Exp/Cntr(USF)=0,0
Exp/Cntr=0.5,0.3

Type RM Length L Ch R = 1 ,1299    ,55.9,56.3,55.2
XS GIS Cut Line= 3
2265767.11074317488869.9277720832265871.35074841488902.567884235
2266177.49689802489044.696515202
#Sta/Elev= 30
       0 2331.32    34.6 2331.76    55.6 2331.05    68.2 2329.68    76.9 2328.22
   105.9  2325.9   127.8 2322.41   158.6 2319.09   175.1 2317.71   191.4 2315.64
   229.4 2313.92   256.4 2313.27   259.4 2312.93   270.2 2310.13   273.3 2309.52
   277.7  2309.3   286.5  2309.5   289.5 2310.07   298.5 2312.39   307.6 2313.99
   321.8 2315.99   335.1 2316.76   344.3 2317.89   352.9 2319.47   400.4  2321.9
     410 2324.77   414.4 2327.01   418.8 2328.69   440.9 2333.17   446.8 2334.04
#Mann= 5 ,-1,0
       0     .06       0  249.23      .1       0   270.2    .045       0
   289.5      .1       0  319.23     .06       0
#XS Ineff= 2 , 0
          257.95  2318.5  301.95            2319
Permanent Ineff=
       F       F
Bank Sta=270.2,289.5
XS Rating Curve= 0 ,0
Exp/Cntr(USF)=0,0
Exp/Cntr=0.5,0.3

Type RM Length L Ch R = 1 ,1243    ,158.3,177.6,193.6
XS GIS Cut Line= 3
2265739.79848943488899.9877079072265848.36278791488943.311454499
 2266098.1520679 489066.73674579
#Sta/Elev= 30
       0 2327.08    26.2    2326    46.4 2324.01      68 2320.12    82.2 2315.84
   111.1 2312.05     148 2310.78   159.9 2311.45   179.1 2311.38   188.1  2310.8
   202.4 2312.66   211.4 2312.43   219.7 2313.17   229.5 2312.17   237.6 2313.57
   246.1 2312.23   256.5 2309.18   268.4 2308.38   274.6 2308.56   279.4 2309.35
   286.2 2311.89   291.3 2313.07   308.5 2314.13   330.2 2316.67   337.8 2318.73
   345.1 2322.55   353.1 2324.59     363 2328.32   375.5 2331.15   395.5 2336.88
#Mann= 4 ,-1,0
       0      .1       0      70     .06       0   256.5    .045       0
   279.4     .06       0
#XS Ineff= 2 , 0
          250.99  2318.5  283.12            2319
Permanent Ineff=
       F       F
Bank Sta=256.5,279.4
XS Rating Curve= 0 ,0
Exp/Cntr(USF)=0,0
Exp/Cntr=0.5,0.3

Type RM Length L Ch R = 1 ,1065    ,206.9,213.5,218.8
XS GIS Cut Line= 3
 2265698.7874977488903.6111218162265820.89919125488975.378520655
2265816.61457042489131.767180813
#Sta/Elev= 30
       0 2325.41    26.8 2324.39    34.7 2323.11    52.6 2316.06    71.2 2309.98
      82 2307.71    89.8 2306.83   105.7 2306.84   121.5 2308.24   129.4 2308.29
   140.8 2307.98   147.4 2306.64   151.4 2306.65   159.4 2308.05   179.5 2308.48
   196.2 2309.68   203.5 2309.29  209.892305.836   215.5  2304.9  229.112305.932
   239.5 2307.03   243.5 2308.57   247.5 2311.72   251.5 2316.12   259.5 2333.24
   263.5 2337.99   275.5 2345.48   283.5 2352.65   286.7 2354.88   298.1 2361.28
#Mann= 5 ,-1,0
       0      .1       0     120     .06       0  161.64      .1       0
  209.89    .045       0  229.11      .1       0
Bank Sta=209.89,229.11
XS Rating Curve= 0 ,0
Exp/Cntr(USF)=0,0
Exp/Cntr=0.3,0.1

Type RM Length L Ch R = 1 ,852     ,197.9,190.9,183.7
XS GIS Cut Line= 2
 2265663.4992458488889.110499183 2265558.2764564489111.518739342
#Sta/Elev= 30
       0  2325.1    17.6 2323.81    22.2 2322.09    26.6 2319.54    31.1 2316.35
    35.5 2312.27    44.3 2304.84    48.8 2303.07      62 2301.95    70.9 2301.69
    75.3 2301.84    79.7 2302.53    83.7 2302.38    88.6 2301.59      93 2300.27
    97.4 2299.92   110.7 2299.09   113.7 2299.96   119.6 2301.61     124 2302.43
   146.1 2301.64   158.8 2302.74   173.8 2302.59   181.5 2302.95   199.2 2304.86
   203.8 2306.17   208.1 2308.31   224.8  2319.2   230.8 2322.43     246 2327.38
#Mann= 4 ,-1,0
       0     .06       0      10      .1       0    97.4    .045       0
   113.7      .1       0
#XS Ineff= 2 , 0
                          160.35         2308.09
Permanent Ineff=
       F       F
Bank Sta=97.4,113.7
XS Rating Curve= 0 ,0
Exp/Cntr(USF)=0,0
Exp/Cntr=0.3,0.1

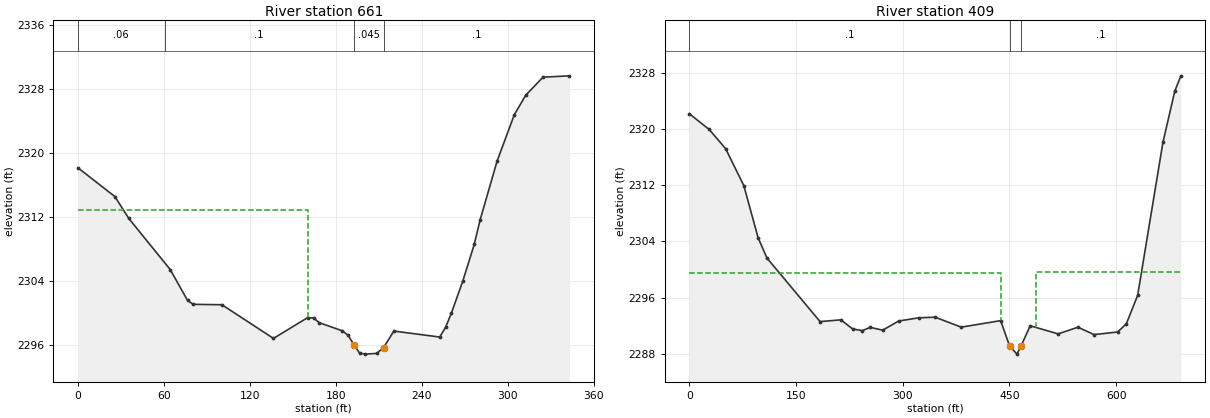
Type RM Length L Ch R = 1 ,661     ,261.4,252.5,241.5
XS GIS Cut Line= 3
 2265445.1142646488743.895058985 2265427.5955212 488791.24333258
2265441.52053888489083.668703971
#Sta/Elev= 30
       0 2318.15    25.8 2314.54    35.5  2311.8    64.4  2305.4    76.5 2301.53
    80.5 2301.04   100.5 2300.99   136.5 2296.77   160.5 2299.39   164.6 2299.31
   168.6 2298.73   184.6 2297.72   188.6 2297.16   192.6    2296   196.6 2294.94
   200.6  2294.8   208.6 2294.89   213.4 2295.63   220.6 2297.69   252.6 2296.94
   256.7 2298.17   260.7 2299.91   268.7 2303.95   276.7 2308.55   280.7 2311.56
   292.7 2319.02   304.7 2324.81   312.7 2327.26   324.7 2329.51   343.2 2329.68
#Mann= 4 ,-1,0
       0     .06       0   60.49      .1       0   192.6    .045       0
   213.4      .1       0
#XS Ineff= 2 , 0
          160.29 2312.84
Permanent Ineff=
       F       F
Bank Sta=192.6,213.4
XS Rating Curve= 0 ,0
Exp/Cntr(USF)=0,0
Exp/Cntr=0.3,0.1

Type RM Length L Ch R = 1 ,409     ,,,
XS GIS Cut Line= 4
2265153.40910273488608.079003058 2265081.4888372488866.277311274
2265309.31534487 489090.03317882 2265412.7139575489082.777135829
#Sta/Elev= 30
       0 2322.16    27.9 2319.92      51 2317.19    76.6 2311.92    96.6 2304.53
   109.1 2301.62   183.8 2292.57   212.9 2292.82   229.5 2291.53   243.1 2291.28
   254.4 2291.75   271.8 2291.35   294.2 2292.65   322.3 2293.11   345.5  2293.2
   382.3 2291.78   437.7 2292.71   450.2  2289.1   460.6 2287.94   466.3 2289.09
   479.2 2291.98   518.5 2290.82   546.3 2291.77     569 2290.72   602.1 2291.09
   614.3 2292.24   630.3 2296.31   665.8 2318.07   682.5 2325.38     691 2327.56
#Mann= 3 ,-1,0
       0      .1       0   450.2    .045       0   466.3      .1       0
#XS Ineff= 2 , 0
          437.58 2299.44  487.96          2299.6
Permanent Ineff=
       F       F
Bank Sta=450.2,466.3
XS Rating Curve= 0 ,0
Exp/Cntr(USF)=0,0
Exp/Cntr=0.3,0.1
LCMann Table=0

Chan Stop Cuts=-1
Use User Specified Reach Order=0
Composite Channel Slope=5